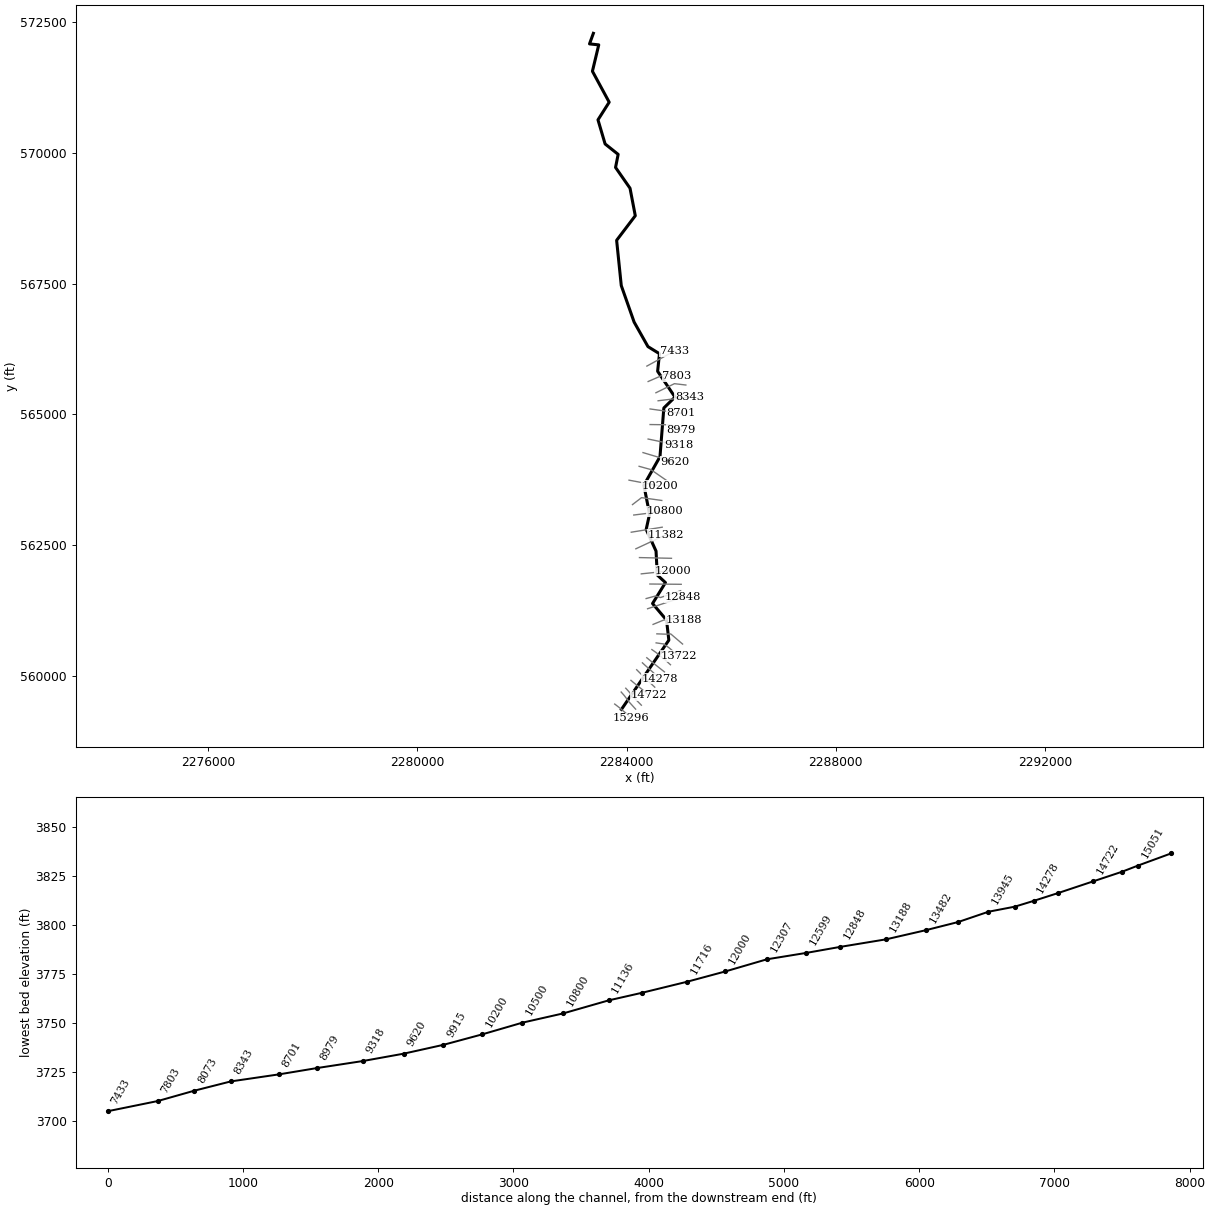
--- FIRSTFK.prj (project) ---

Proj Title=FIRSTFK
Current Plan=p01
Default Exp/Contr=0,0
English Units
Geom File=g01
Flow File=f01
Plan File=p01
BEGIN DESCRIPTION:
----------MODEL BY WOOD PLC 2022----------
AFH study
Randolph County, WV
HEC-RAS Version: RAS 6.2
Vertical Datum: NAVD88
Projection: NAD 1983 StatePlane West Virginia S FIPS 4702 (US Feet)
Terrain: 1-meter LIDAR (FEMA Region III 3DEP collected 2016-2018)
Land Use: 2019 NLCD
Hydrologic Method:
WV SIR2010-5033 regression equations
Additional Model Notes:
Upstream extent in Pocahontas County.  10 shared XS's and river line with Pocahontas County model.
END DESCRIPTION:
DSS Export Rating Curves= 0
DSS Export Rating Curve Sorted= 0
DSS Export Volume Flow Curves= 0
DXF OffsetX= 0
DXF OffsetY= 0
DXF ScaleX= 0
DXF ScaleY= 0

--- FIRSTFK.p01 (plan) ---

Plan Title=Floodplain
Program Version=6.20
Short Identifier=Floodplain
Geom File=g01
Flow File=f01
Subcritical Flow
K Sum by GR= 0
Std Step Tol= 0.01
Critical Tol= 0.01
Num of Std Step Trials= 20
Max Error Tol= 0.3
Flow Tol Ratio= 0.001
Split Flow NTrial= 30
Split Flow Tol= 0.02
Split Flow Ratio= 0.02
Log Output Level= 0
Friction Slope Method= 1
Unsteady Friction Slope Method= 2
Unsteady Bridges Friction Slope Method= 1
Parabolic Critical Depth
Global Vel Dist= 0 , 0 , 0
Global Log Level= 0
CheckData=True
Encroach Param=-1 ,0,0, 0
Mapping Interval=1HOUR
Computation Time Step Use Courant=        0
Computation Time Step Use Time Series=    0
Computation Time Step Count To Double=0
Computation Time Step Max Doubling=0
Computation Time Step Max Halving=0
Computation Time Step Residence Courant=0
Run HTab= 0
Run UNet= 0
Run Sediment= 0
Run PostProcess= 0
Run WQNet= 0
Run RASMapper=-1
UNET Theta= 0
UNET Theta Warmup= 0
UNET ZTol= 0
UNET ZSATol= 0
UNET MxIter= 0
UNET Max Iter WO Improvement= 0
UNET MaxInSteps= 0
UNET DtIC= 0
UNET DtMin= 0
UNET MaxCRTS= 0
UNET WFStab= 0
UNET SFStab= 0
UNET WFX= 1
UNET SFX= 1
UNET Gravity=32.174
UNET 1D Methodology=Finite Difference
UNET DSS MLevel= 1
UNET Pardiso=0
UNET DZMax Abort= 0
UNET Use Existing IB Tables= 0
UNET Froude Reduction=False
UNET Froude Limit= 0
UNET Froude Power= 0
UNET D1 Cores= 0
UNET WindReference=Eulerian
UNET WindDragFormulation=Hsu (1988)
UNET D2 Coriolis=0
UNET D2 Cores= 0
UNET D2 Theta= 1
UNET D2 Theta Warmup= 1
UNET D2 Z Tol= 0.01
UNET D2 Volume Tol= 0.01
UNET D2 Max Iterations= 20
UNET D2 Equation= 0
UNET D2 RampUpFraction=0.1
UNET D2 TimeSlices= 1
UNET D2 Turbulence Formulation=Non-Conservative (original)
UNET D2 Eddy Viscosity=0.3
UNET D2 Transverse Eddy Viscosity=0.1
UNET D2 Smagorinsky Mixing=0
UNET D2 BCVolumeCheck=0
UNET D2 Cores=0
UNET D2 SolverType=PARDISO (Direct)
UNET D2 Minimum Iterations= 2147483647
UNET D2 Maximum Iterations= 2147483647
UNET D2 Restart Number= 10
UNET D2 Relaxation Coeff=1.3
UNET D2 SOR Precondition Iterations= 10
UNET D2 ILUT Maximum Fill= 8
UNET D2 ILUT Tolerance=1E-08
UNET D1D2 MaxIter= 0
UNET D1D2 ZTol=0.01
UNET D1D2 QTol=0.1
UNET D1D2 MinQTol=1
Write IC File= 0
Write IC File at Fixed DateTime=0
Write IC File at Sim End=0
Echo Input=False
Echo Parameters=False
Echo Output=False
Write Detailed= 0
HDF Write Warmup=0
HDF Write Time Slices=0
HDF Flush=0
HDF Compression= 1
HDF Chunk Size= 1
HDF Spatial Parts= 1
HDF Use Max Rows=0
HDF Fixed Rows= 1
Calibration Method= 0
Calibration Iterations= 20
Calibration Max Change=0.05
Calibration Tolerance=0.2
Calibration Maximum=1.5
Calibration Minimum=0.5
Calibration Optimization Method= 1
WQ AD Non Conservative
WQ ULTIMATE=-1
WQ Max Comp Step=1HOUR
WQ Output Interval=15MIN
WQ Output Selected Increments= 0
WQ Output face flow=0
WQ Output face velocity=0
WQ Output face area=0
WQ Output face dispersion=0
WQ Output cell volume=0
WQ Output cell surface area=0
WQ Output cell continuity=0
WQ Output cumulative cell continuity=0
WQ Output face conc=0
WQ Output face dconc_dx=0
WQ Output face courant=0
WQ Output face peclet=0
WQ Output face adv mass=0
WQ Output face disp mass=0
WQ Output cell mass=0
WQ Output cell source sink temp=0
WQ Output nsm pathways=0
WQ Output nsm derived pathways=0
WQ Create Restart=0
WQ Fixed Restart=0
WQ System Summary=0
WQ Write To DSS=0
Sorting and Armoring Iterations= 10
XS Update Threshold= 0.02
Bed Roughness Predictor= 0
Hydraulics Update Threshold= 0.02
Energy Slope Method= 1
Volume Change Method= 1
Sediment Retention Method= 0
Sediment TS Multiplier= 1
Warm Up Method= 0
XS Weighting Method= 0
Number of US Weighted Cross Sections= 1
Number of DS Weighted Cross Sections= 1
Upstream XS Weight=0
Main XS Weight=1
Downstream XS Weight=0
Number of DS XS's Weighted with US Boundary= 1
Upstream Boundary Weight= 1
Weight of XSs Associated with US Boundary= 0
Number of US XS's Weighted with DS Boundary= 1
Downstream Boundary Weight= 0.5
Weight of XSs Associated with DS Boundary= 0.5
Percentile Method= 0
Sediment Output Level= 3
Mass or Volume Output= 0
Output Increment Type= 1
Profile and TS Output Increment= 1
Transport Output Increment 1
XS Output Flag= 0
XS Output Increment= 10
Read HDF5 Sediment Hotstart= 0
Sediment Hotstart Type= 0
Write Gradation File= 0
Read Gradation Hotstart= 0
Write HDF5 File= 1
Write Binary Output= 1
Write DSS Sediment File= 0
DSS Sediment Output Type= 1
SV Curve= 0
Specific Gage Flag= 0
Subcell Erosion Methods= 0
Subcell Deposition Methods= 0
Advection Scheme= 1
Matrix Solver= 0
Implicit Weighting Factor= 1
Maximum Outer Loop Convergence Iterations= 5
Convergence Maximum Absolute= 0.001
Convergence RMSE= 0.0001
Grain Fractions Max Abs Error= 0.001
Max Subgrid Regions= 1
Max Subgrid Length Scale= 3.402823E+38
Initial Layer Thickness= 3.402823E+38
Min Layer Thickness= 3.402823E+38
Max Layer Thickness= 3.402823E+38
Number of Layers= 5

--- FIRSTFK.f01 (steady flow) ---

Flow Title=Flow
Program Version=6.20
Number of Profiles= 1
Profile Names=P100yr
River Rch & RM=FIRSTFK,Main,15296
    1170
River Rch & RM=FIRSTFK,Main,11382
    1300
River Rch & RM=FIRSTFK,Main,8073
    1800
Boundary for River Rch & Prof#=FIRSTFK,Main            , 1
Up Type= 0
Dn Type= 3
Dn Slope=0.00439
DSS Import GetInterval= 0
DSS Import GetPeak= 0
DSS Import FillOption= 0

--- FIRSTFK.g01 (geometry) ---

Geom Title=Geometry
Program Version=6.20

River Reach=FIRSTFK         ,Main
Reach XY= 30
2283902.42117289559356.9025110452284808.83256115560680.786403835
2284764.79800001561064.4679999952284497.41600004561381.101999998
2284744.37800004561781.2750000062284588.09900001561926.443000019
 2284564.1106593562383.5078496782284375.65428649562798.700796008
2284440.18200003563092.4160000092284331.15400001563643.109999999
2284639.48800005564189.6379999972284713.09900002565120.193000019
2284926.29300003 565328.527000012284594.34900001565822.276999995
2284629.76500002566157.6930000192284409.62599999566293.804000005
2284144.90500002566762.7979999932283899.21000004567461.166000009
2283810.46000004568326.1829999982284167.10100001568796.209000021
2284066.74200003569322.079000011     2283789.861569719.736000016
2283839.62599999569969.7650000012283590.21700002 570168.84800002
2283453.98483832 570629.946474882283668.13500002570967.447000012
2283347.64899999571559.2880000172283468.49583176572063.421617836
2283292.09300002572082.2039999962283365.69761476572284.101556584

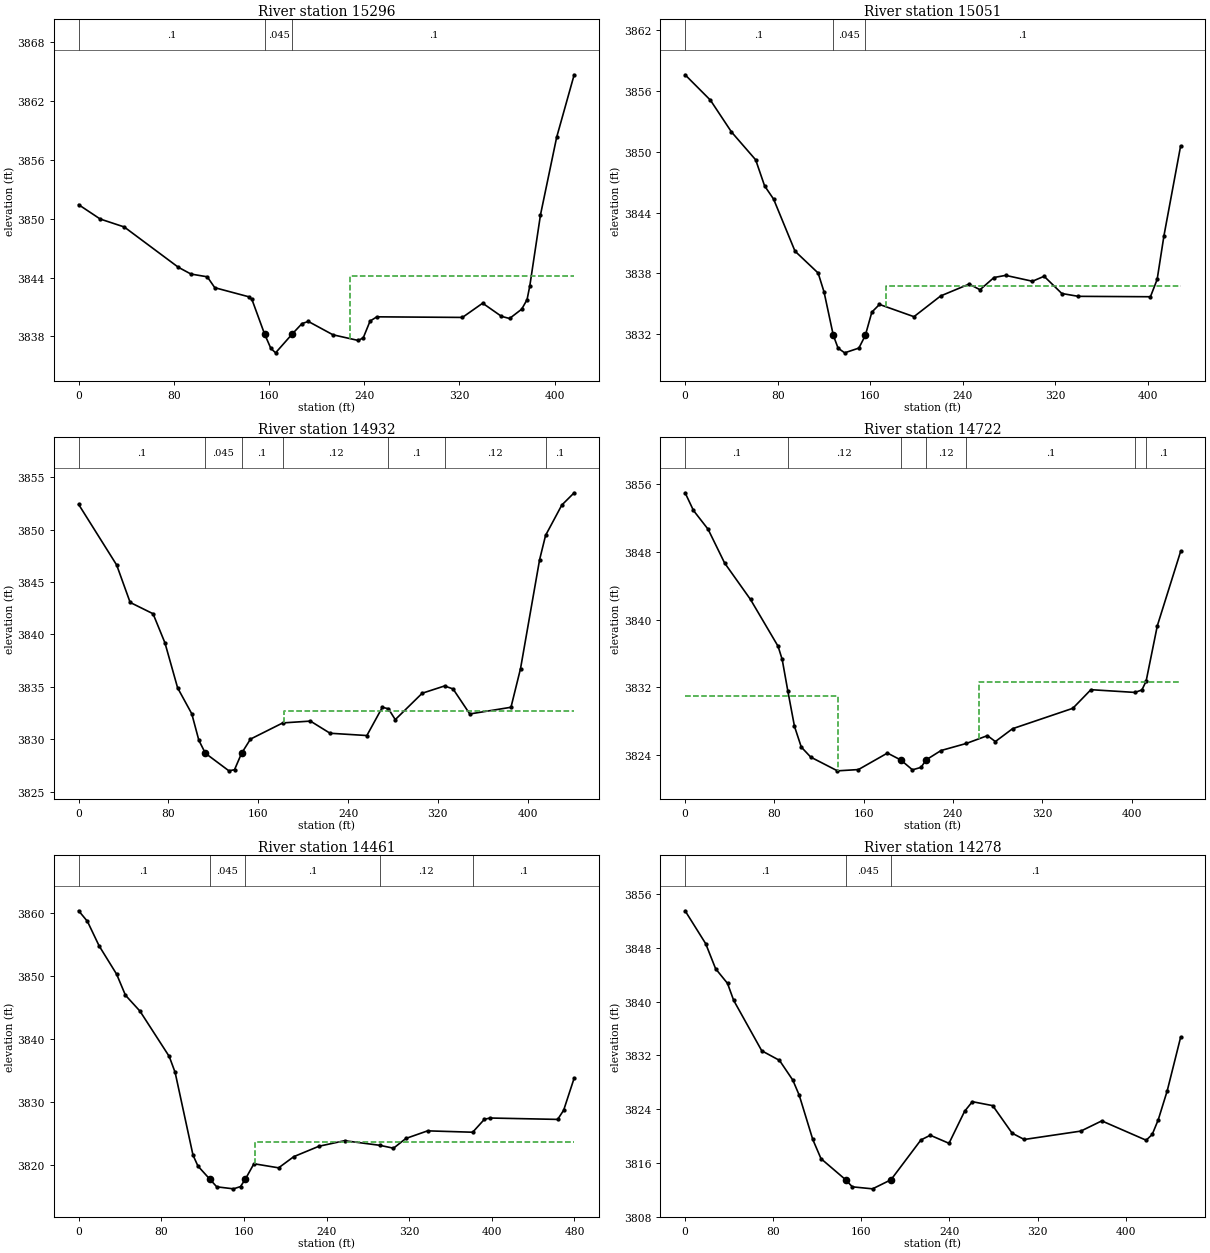
Type RM Length L Ch R = 1 ,15296   ,244.4,244.4,244.4
XS GIS Cut Line= 4
2283773.82990032 559459.300790362283863.17969556559390.257766765
2283985.02032544559286.6932313732284086.55418366559185.159373146
#Sta/Elev= 30
       0 3851.43    18.1 3849.97    38.3 3849.16    83.8 3845.05    94.4 3844.36
   108.1 3844.08   114.4 3842.97   142.8 3842.05   145.6 3841.78   156.2 3838.26
   161.5 3836.79   165.5 3836.33   179.7 3838.28   187.7 3839.31     193 3839.53
   213.7 3838.17     235 3837.59   239.2 3837.87   244.9 3839.57   250.6    3840
   322.5 3839.94   339.5 3841.39   355.3 3840.05   362.1 3839.83   372.3 3840.78
   376.8 3841.75   379.1 3843.14   388.1  3850.4   401.7 3858.31   416.4 3864.67
#Mann= 3 ,-1,0
       0      .1       0   156.2    .045       0   179.7      .1       0
#XS Ineff= 2 , 0
                          228.01         3844.19
Permanent Ineff=
       F       F
Bank Sta=156.2,179.7
XS Rating Curve= 0 ,0
Exp/Cntr=0.3,0.1

Type RM Length L Ch R = 1 ,15051   ,118.9,118.9,118.9
XS GIS Cut Line= 4
2283897.70120736559688.7673099532283956.59084513559621.754963523
2284052.03267187559495.8529793222284173.87330174559361.828286462
#Sta/Elev= 30
       0 3857.61    21.9  3855.1    40.1 3851.96      61 3849.21    68.7 3846.64
    76.5 3845.33      95 3840.19     115 3838.03   120.1 3836.16   128.1 3831.88
   132.2 3830.62   137.9 3830.15   150.2 3830.62   155.8 3831.88   161.4 3834.17
     168 3834.93   197.8 3833.72   220.9 3835.77   245.5 3836.94   254.9 3836.38
     267 3837.59   277.1  3837.8   300.2 3837.22   310.3 3837.71   325.6 3836.01
   339.8 3835.73   402.2 3835.69     408  3837.4   413.9 3841.73   428.3 3850.59
#Mann= 3 ,-1,0
       0      .1       0   128.1    .045       0   155.8      .1       0
#XS Ineff= 2 , 0
                          173.26         3836.75
Permanent Ineff=
       F       F
Bank Sta=128.1,155.8
XS Rating Curve= 0 ,0
Exp/Cntr=0.3,0.1

Type RM Length L Ch R = 1 ,14932   ,210.5,210.5,210.5
XS GIS Cut Line= 4
2283985.02032544559761.8716878772284033.75657738559709.074081599
 2284119.0450183559605.5095462072284283.52986862 559436.96334155
#Sta/Elev= 30
       0 3852.42    33.9 3846.63    45.9 3843.06    66.3 3841.98    76.9  3839.2
    88.2  3834.9   100.8 3832.43   107.1  3829.9   112.9 3828.66   133.9 3826.98
   138.9 3827.09   145.2 3828.66   153.1 3830.01  181.853831.555   206.5 3831.73
     224 3830.57   256.8 3830.35   270.6 3833.05  276.023832.906   282.1 3831.87
   306.1 3834.39  326.023835.084   333.6  3834.8   348.5 3832.41   385.2 3833.05
   393.7 3836.74   410.7 3847.14  416.023849.461   430.5 3852.36   441.5 3853.53
#Mann= 7 ,-1,0
       0      .1       0   112.9    .045       0   145.2      .1       0
  181.85     .12       0  276.02      .1       0  326.02     .12       0
  416.02      .1       0
#XS Ineff= 2 , 0
                           182.6         3832.68
Permanent Ineff=
       F       F
Bank Sta=112.9,145.2
XS Rating Curve= 0 ,0
Exp/Cntr=0.3,0.1

Type RM Length L Ch R = 1 ,14722   ,261,261,261
XS GIS Cut Line= 4
 2284084.5235065559912.1417980532284139.35178994559865.436223269
2284311.95934893 559727.350176082284423.64659298559625.816317852
#Sta/Elev= 30
       0 3855.01     7.5 3852.92    20.6  3850.7    35.4 3846.71    58.6  3842.4
    83.3 3836.87      87 3835.31   92.023831.608      98 3827.41   104.1 3824.96
   112.6 3823.77   136.5 3822.15   155.3  3822.3   181.3 3824.25   193.3 3823.43
   203.7 3822.27   211.4 3822.56     216 3823.45   229.3 3824.55  252.023825.388
   270.9 3826.31     278 3825.61   293.4 3827.13   347.4 3829.54   363.6 3831.74
  403.073831.417   409.3 3831.71  413.07 3832.75   423.1 3839.29     444 3848.08
#Mann= 7 ,-1,0
       0      .1       0   92.02     .12       0   193.3    .045       0
     216     .12       0  252.02      .1       0  403.07     .12       0
  413.07      .1       0
#XS Ineff= 2 , 0
          136.96    3831  263.48         3832.59
Permanent Ineff=
       F       F
Bank Sta=193.3,216
XS Rating Curve= 0 ,0
Exp/Cntr=0.3,0.1

Type RM Length L Ch R = 1 ,14461   ,182.6,182.6,182.6
XS GIS Cut Line= 4
2284194.18007338560115.2095145082284255.10038832560054.289199572
2284395.21711267559918.2338295472284539.39519136559782.178459523
#Sta/Elev= 30
       0 3860.36     8.5 3858.68    19.8 3854.79    36.8 3850.27    45.3 3846.94
    59.4  3844.4    87.7  3837.2    93.4 3834.67   110.7 3821.52   115.5 3819.77
   126.8 3817.72   133.7 3816.47   149.9 3816.15   156.7 3816.51   161.4  3817.7
   169.7 3820.14   193.6 3819.49   208.3 3821.27   232.6 3822.92   257.4  3823.8
  291.463823.072   304.8 3822.61   316.8 3824.16   337.8 3825.37  381.463825.152
   392.8 3827.21   398.3 3827.41   463.7 3827.19   469.5 3828.64   479.7 3833.76
#Mann= 5 ,-1,0
       0      .1       0   126.8    .045       0   161.4      .1       0
  291.46     .12       0  381.46      .1       0
#XS Ineff= 2 , 0
                           171.1         3823.67
Permanent Ineff=
       F       F
Bank Sta=126.8,161.4
XS Rating Curve= 0 ,0
Exp/Cntr=0.3,0.1

Type RM Length L Ch R = 1 ,14278   ,139,139,139
XS GIS Cut Line= 4
2284303.83664027560247.2035302032284358.66492371 560196.43660109
2284498.78164807560072.5652940522284634.83701809559942.601955522
#Sta/Elev= 30
       0 3853.53    18.7 3848.63    27.7  3844.9    38.5 3842.72    44.1 3840.19
    69.6 3832.68    85.7 3831.25    97.8 3828.31   103.6 3826.07   115.9 3819.48
   123.4 3816.61   145.8 3813.47   151.8 3812.42   170.2 3812.12   186.9 3813.47
   214.1  3819.4   222.6  3820.1   239.6  3818.9   253.8 3823.68   260.8  3825.1
   279.3 3824.51   296.9 3820.41   307.9 3819.47   359.3 3820.72   378.3 3822.24
   418.6 3819.36   424.1 3820.22   429.6 3822.42   437.7 3826.71   449.9  3834.7
#Mann= 3 ,-1,0
       0      .1       0   145.8    .045       0   186.9      .1       0
Bank Sta=145.8,186.9
XS Rating Curve= 0 ,0
Exp/Cntr=0.3,0.1

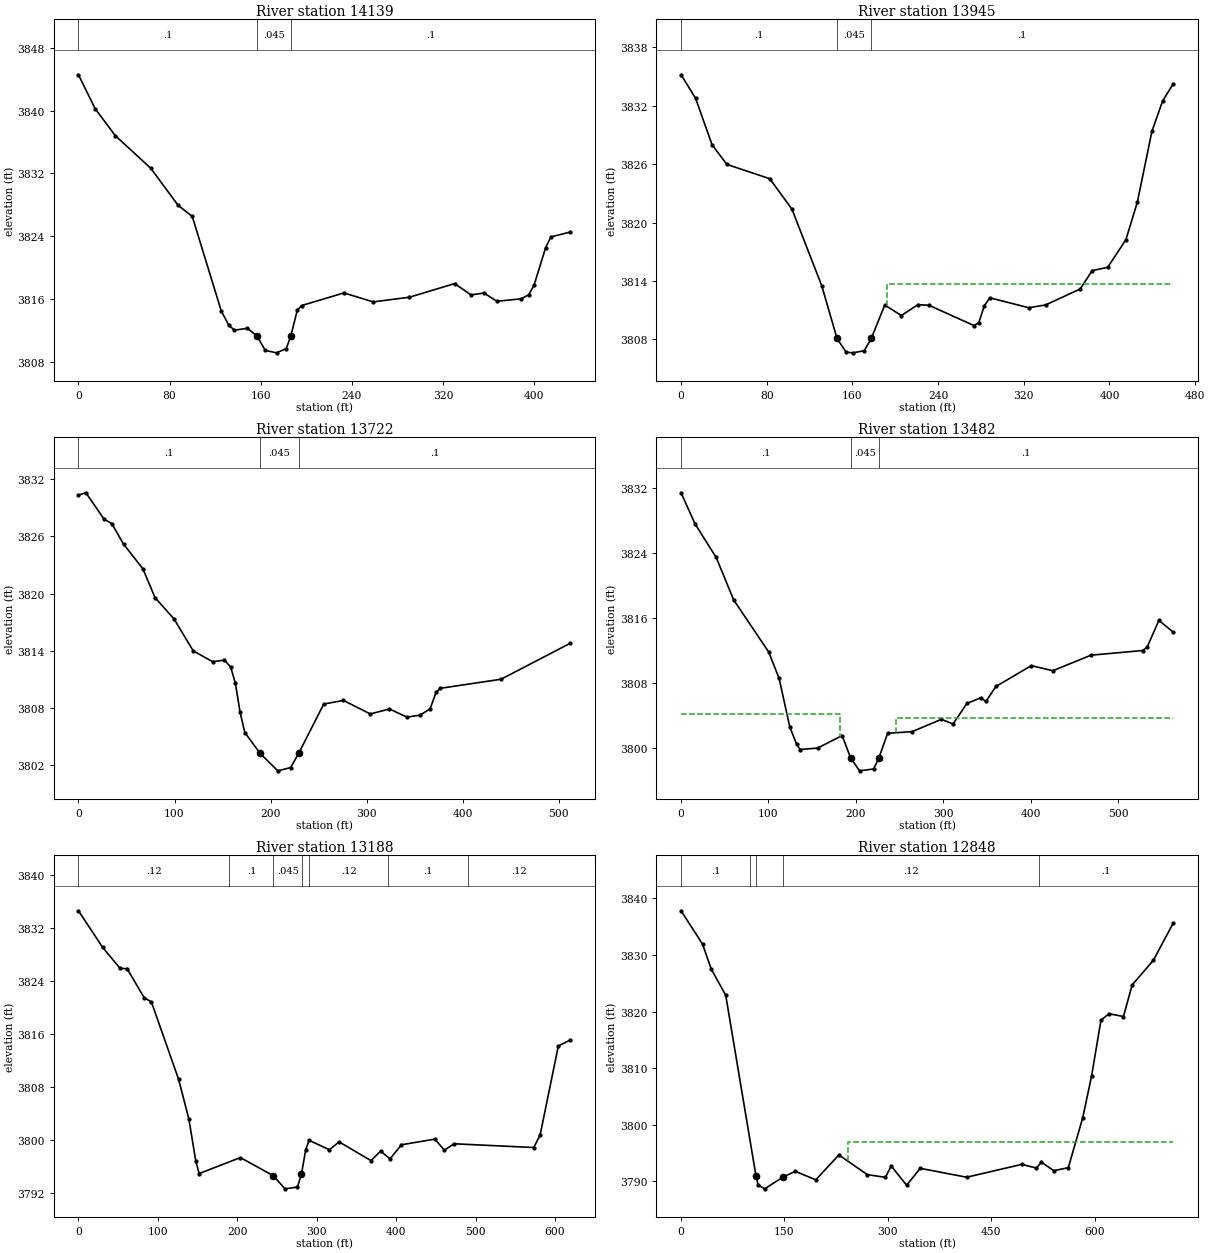
Type RM Length L Ch R = 1 ,14139   ,194.1,194.1,194.1
XS GIS Cut Line= 4
2284387.09440402560344.6760341022284466.29081343560279.694364836
2284620.62227794560155.8230577992284724.18681333560074.595971217
#Sta/Elev= 30
       0 3844.55    14.6 3840.25    32.4  3836.8    63.5 3832.66    87.5 3827.95
    99.9 3826.54   125.5 3814.47     132 3812.71   136.9 3812.07   148.3 3812.31
   156.8 3811.33     164  3809.5   173.9 3809.19   182.4 3809.72   186.5 3811.33
   192.1 3814.61   195.9  3815.2   233.1 3816.81   258.7 3815.67   290.5 3816.26
   330.4    3818   344.6 3816.55     356  3816.8   367.4 3815.75   388.9 3816.06
   395.4 3816.59     400 3817.79   410.2 3822.56   414.8 3823.93     432 3824.56
#Mann= 3 ,-1,0
       0      .1       0   156.8    .045       0   186.5      .1       0
Bank Sta=156.8,186.5
XS Rating Curve= 0 ,0
Exp/Cntr=0.3,0.1

Type RM Length L Ch R = 1 ,13945   ,223.4,223.4,223.4
XS GIS Cut Line= 4
2284484.56690791560501.0381757712284567.82467166   560442.148538
2284744.49358498560297.9704593172284839.93541171560210.651341242
#Sta/Elev= 30
       0 3835.17    13.6 3832.75    28.9    3828    42.7 3825.97    82.8  3824.5
   103.5 3821.38   131.3 3813.53   145.6  3808.1   154.1 3806.69   160.5 3806.62
   171.1 3806.84   177.7 3808.12   190.2 3811.53   205.7 3810.45   221.2 3811.57
   231.5  3811.5   273.5 3809.42     278 3809.72   283.1 3811.44   288.3 3812.27
   324.7 3811.25   340.4 3811.54   372.7 3813.18   383.8 3815.06   398.3  3815.4
   415.3 3818.23     426 3822.08   439.7  3829.4   449.7  3832.5  459.37 3834.21
#Mann= 3 ,-1,0
       0      .1       0   145.6    .045       0   177.7      .1       0
#XS Ineff= 2 , 0
                          191.95         3813.65
Permanent Ineff=
       F       F
Bank Sta=145.6,177.7
XS Rating Curve= 0 ,0
Exp/Cntr=0.3,0.1

Type RM Length L Ch R = 1 ,13722   ,239.6,239.6,239.6
XS GIS Cut Line= 4
 2284565.7939945560628.9708371382284707.94139601560608.664065492
 2284817.5979629 560531.498333242284994.26687621560377.166868734
#Sta/Elev= 30
       0 3830.33     7.8 3830.57    26.6 3827.81    34.7 3827.34    46.9 3825.19
    67.1 3822.59    79.7 3819.57    99.4 3817.34   119.6 3813.97   139.8 3812.84
     152 3813.01   158.5 3812.27   163.4 3810.57   168.3 3807.53   173.2 3805.41
   189.1 3803.23   207.5 3801.39   220.9 3801.73   229.3 3803.23   255.4  3808.4
   275.9 3808.78   303.8 3807.36   323.8 3807.88     342 3807.03   355.5 3807.23
   366.1 3807.89   372.4 3809.64   376.7 3810.05   439.9    3811  512.26 3814.79
#Mann= 3 ,-1,0
       0      .1       0   189.1    .045       0   229.3      .1       0
Bank Sta=189.1,229.3
XS Rating Curve= 0 ,0
Exp/Cntr=0.3,0.1

Type RM Length L Ch R = 1 ,13482   ,293.4,293.4,293.4
XS GIS Cut Line= 4
2284580.00873465560801.5783961242284744.49358498560795.486364631
 2284846.0274432 560799.547718962285071.43260847560606.633388328
#Sta/Elev= 30
       0  3831.4      16 3827.58    40.2 3823.45    60.2 3818.23   100.2 3811.84
   112.2 3808.58   124.3 3802.67   132.3 3800.46   136.3 3799.84   156.3 3800.02
   184.3 3801.56     194  3798.8   204.3 3797.22   220.3 3797.45   226.3 3798.79
   236.3 3801.83   264.4 3802.04   297.8 3803.55   311.2 3802.98     327  3805.5
   342.7 3806.19   348.9 3805.75   360.2 3807.59   400.7 3810.15   425.4 3809.53
   469.1 3811.44   528.2 3812.01   533.3 3812.44   546.7 3815.72   562.9 3814.28
#Mann= 3 ,-1,0
       0      .1       0     194    .045       0   226.3      .1       0
#XS Ineff= 2 , 0
          182.03 3804.17   246.3         3803.76
Permanent Ineff=
       F       F
Bank Sta=194,226.3
XS Rating Curve= 0 ,0
Exp/Cntr=0.3,0.1

Type RM Length L Ch R = 1 ,13188   ,340.8,340.8,340.8
XS GIS Cut Line= 3
2284507.52755477560982.0526943672284796.64012094561100.657857331
2285102.13818859561070.384743934
#Sta/Elev= 30
       0 3834.64    30.5 3829.09    52.6 3825.91    61.2 3825.89    82.8 3821.48
    91.8 3820.86   126.1 3809.14   139.1 3803.09   147.7 3796.78     152 3794.88
   203.9  3797.3245.31153794.556   260.1 3792.57   275.7 3792.84280.71633794.771
   286.1 3798.45   290.4 3799.91     316 3798.48   328.1 3799.68   368.3 3796.84
   380.4 3798.27   392.4 3797.11   406.7 3799.24   448.7 3800.09   460.8 3798.41
   472.8 3799.39   573.3 3798.82   581.3 3800.73   604.2 3814.17   619.5 3815.11
#Mann= 7 ,-1,0
       0     .12       0     190      .1       0   245.5    .045       0
   281.8      .1       0     290     .12       0     390      .1       0
     490     .12       0
Bank Sta=245.3115,280.7163
XS Rating Curve= 0 ,0
Exp/Cntr(USF)=0,0
Exp/Cntr=0.3,0.1

Type RM Length L Ch R = 1 ,12848   ,248.9,248.9,248.9
XS GIS Cut Line= 2
2284402.58000503561281.6231716722285080.59367223 561504.93227511
#Sta/Elev= 30
       0 3837.78    31.2 3831.89    43.8 3827.49    64.8 3822.89   108.73790.977
   111.8 3789.36   121.3  3788.7   147.93790.784   165.9 3791.79   195.4 3790.29
     229 3794.68   270.2 3791.21   296.5 3790.73   304.9 3792.75   327.2 3789.33
     347 3792.32   414.4 3790.75   494.4 3793.02   515.5 3792.36   522.8 3793.41
   540.7  3791.9   561.8 3792.44   582.8 3801.27   595.5 3808.57   609.2 3818.45
   620.8 3819.61   641.8 3819.11   654.4 3824.68   685.2 3829.04   713.8 3835.55
#Mann= 5 ,-1,0
       0      .1       0     100     .12       0   108.7    .045       0
   147.9     .12       0     520      .1       0
#XS Ineff= 2 , 0
                        241.9928            3797
Permanent Ineff=
       F       F
Bank Sta=108.7,147.9
XS Rating Curve= 0 ,0
Exp/Cntr(USF)=0,0
Exp/Cntr=0.3,0.1

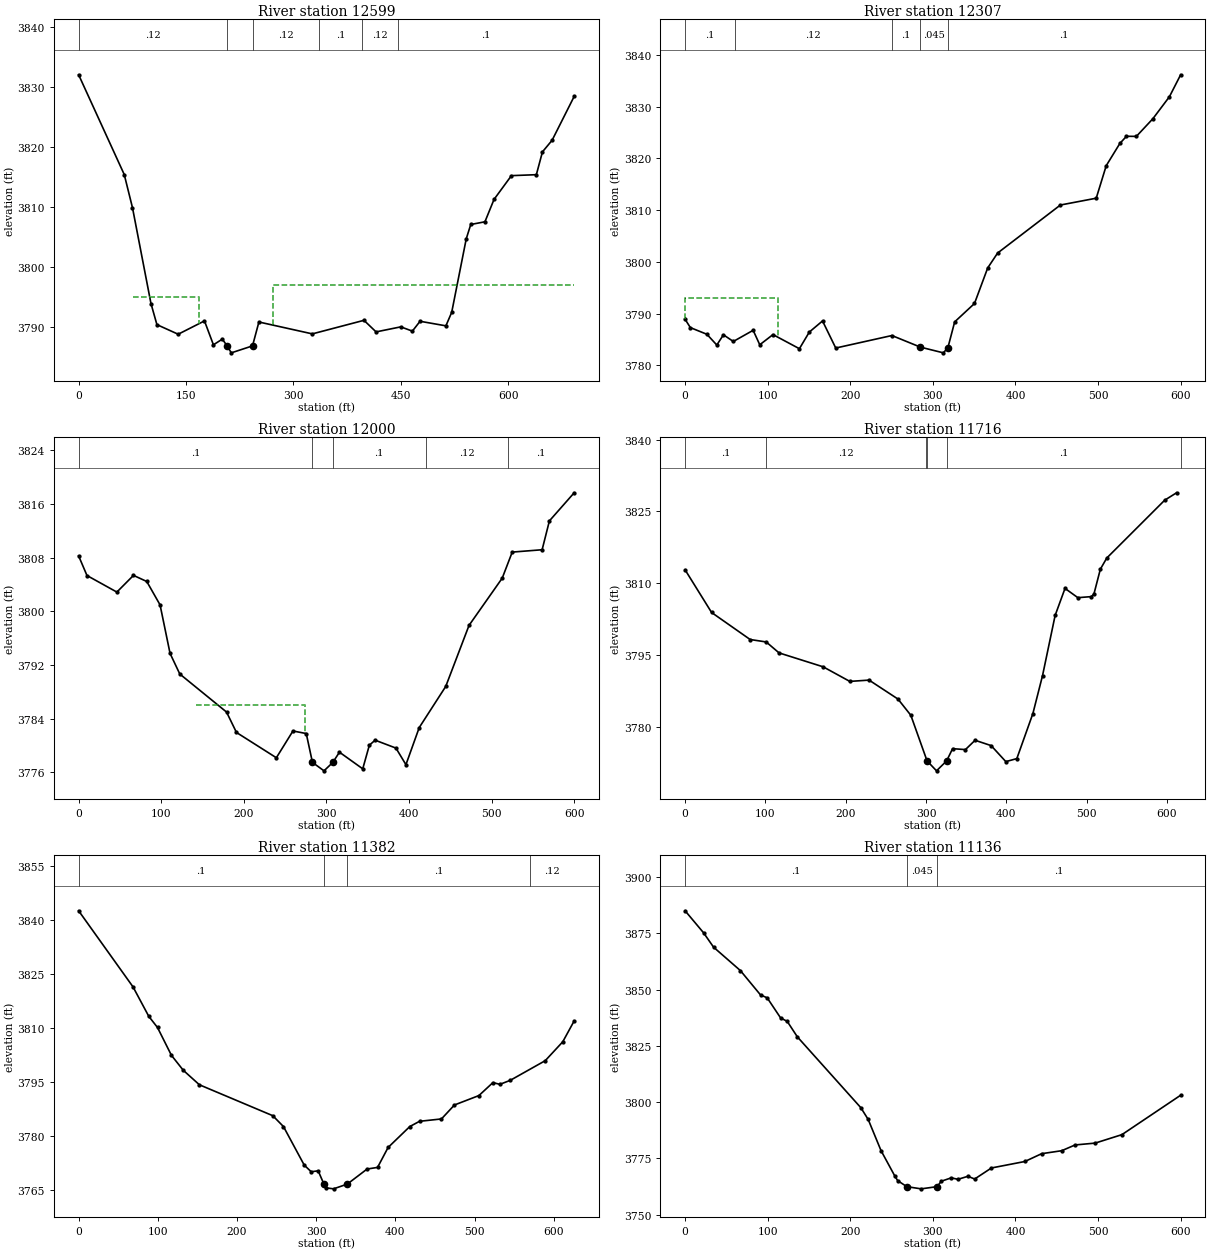
Type RM Length L Ch R = 1 ,12599   ,292.2,292.2,292.2
XS GIS Cut Line= 4
 2284374.7696028 561476.295987322284553.08335831561525.373167736
2284649.60181312561495.926859487 2285034.1872306561626.220851836
#Sta/Elev= 30
       0    3832    63.7 3815.37    75.2 3809.84     101 3793.88   109.3 3790.36
     139 3788.76   175.7 3790.98   188.2    3787   200.7 3787.95   207.4 3786.79
   213.2 3785.66   242.8 3786.82   251.7  3790.8   326.3 3788.82   398.4 3791.08
   415.3 3789.15   449.8 3789.99     466 3789.28   476.7 3790.92   512.8 3790.16
   520.9 3792.41   541.2 3804.66   547.5 3807.05   567.3  3807.5     580 3811.23
   604.3 3815.19   639.1 3815.35   647.6 3819.15   661.1 3821.09   691.9 3828.39
#Mann= 6 ,-1,0
       0     .12       0   207.4    .045       0   242.8     .12       0
  335.85      .1       0  395.85     .12       0  445.85      .1       0
#XS Ineff= 2 ,-1
76.49941167.7663    3795271.2538   691.9    3797
Permanent Ineff=
       F       F
Bank Sta=207.4,242.8
XS Rating Curve= 0 ,0
Exp/Cntr(USF)=0,0
Exp/Cntr=0.3,0.1

Type RM Length L Ch R = 1 ,12307   ,306.6,306.6,306.6
XS GIS Cut Line= 2
2284445.79801268561754.4238592092285045.77239958561748.879937652
#Sta/Elev= 30
       0 3788.88     6.4 3787.27    26.4 3785.98    38.4  3783.9    46.4 3785.88
    58.4 3784.59    82.4 3786.75    90.4 3783.95   106.4 3785.92   138.4 3783.19
   150.4 3786.41   166.4 3788.56   182.4 3783.32   250.4 3785.74     285 3783.49
   312.7 3782.39   318.23783.387   326.4 3788.38   350.4 3791.94   366.4 3798.82
   378.4  3801.7   454.4 3810.99   497.8 3812.31   509.9  3818.6   526.4  3822.9
   534.4 3824.29   546.4 3824.27   566.4 3827.69   586.4 3831.94     600 3836.19
#Mann= 5 ,-1,0
       0      .1       0      60     .12       0     250      .1       0
     285    .045       0   318.2      .1       0
#XS Ineff= 2 , 0
        112.0656    3793
Permanent Ineff=
       F       F
Bank Sta=285,318.2
XS Rating Curve= 0 ,0
Exp/Cntr(USF)=0,0
Exp/Cntr=0.3,0.1

Type RM Length L Ch R = 1 ,12000   ,283.7,283.7,283.7
XS GIS Cut Line= 2
2284282.09191831561948.6109241572284878.78629932562011.506199546
#Sta/Elev= 30
       0 3808.25    10.1 3805.33    46.3 3802.86    66.4 3805.35    82.5 3804.44
    98.6 3800.95   110.7 3793.72   122.5 3790.65   179.1 3784.98   191.1 3781.94
   239.4 3778.17   259.5 3782.16   275.6 3781.78   283.1 3777.48   297.1 3776.22
   307.8 3777.48   315.8    3779     344 3776.52     352 3780.04     359 3780.79
   384.2 3779.61   396.3 3777.14   412.4 3782.67   444.5  3788.8   472.7  3797.9
   512.9 3804.94     525 3808.82   561.2 3809.17     570 3813.47     600 3817.66
#Mann= 5 ,-1,0
       0      .1       0   283.1    .045       0   307.8      .1       0
     420     .12       0     520      .1       0
#XS Ineff= 1 ,-1
142.2781274.5946    3786
Permanent Ineff=
       F
Bank Sta=283.1,307.8
XS Rating Curve= 0 ,0
Exp/Cntr(USF)=0,0
Exp/Cntr=0.3,0.1

Type RM Length L Ch R = 1 ,11716   ,334.6,334.6,334.6
XS GIS Cut Line= 2
2284247.16893372562259.8949679532284858.97680795562246.065777097
#Sta/Elev= 30
       0 3812.84      33 3803.95      81 3798.32     101 3797.81     117 3795.53
   171.9 3792.63   205.1 3789.59   229.1 3789.86   265.1 3785.91   281.1 3782.53
   301.33773.027   313.1 3770.95   325.7 3773.03   333.1 3775.57   349.1 3775.38
   361.1 3777.32   381.1 3776.21   399.4 3772.87   413.1  3773.5   433.1 3782.89
   445.1 3790.79   460.8 3803.34   473.1 3808.97   489.1 3807.04   505.9 3807.26
   509.1 3807.79   517.1 3812.97   525.1  3815.3   597.2 3827.35     612  3828.9
#Mann= 6 ,-1,0
       0      .1       0  100.36     .12       0  300.36      .1       0
   301.3    .045       0   325.7      .1       0  617.09     .12       0
Bank Sta=301.3,325.7
XS Rating Curve= 0 ,0
Exp/Cntr(USF)=0,0
Exp/Cntr=0.3,0.1

Type RM Length L Ch R = 1 ,11382   ,245.5,245.5,245.5
XS GIS Cut Line= 2
2284177.90688305562427.7665965282284745.26033903562691.921980134
#Sta/Elev= 30
       0 3842.64    68.7 3821.47    88.6 3813.28    99.6 3810.18   117.2 3802.44
   132.2 3798.27   152.5 3794.25   245.2 3785.65   258.7 3782.62   284.9 3771.91
   293.7 3770.06   302.5 3770.32   309.83766.612   312.9 3765.57   321.9 3765.31
   339.33766.631   364.3 3770.82   377.5 3771.27   390.8 3776.81   418.2 3782.63
   430.5 3784.09   458.2 3784.75   474.6 3788.63   505.5 3791.25   523.2 3794.86
     532 3794.37   545.2  3795.5   589.3 3800.96   611.4 3806.21   625.8 3812.01
#Mann= 4 ,-1,0
       0      .1       0   309.8    .045       0   339.3      .1       0
     570     .12       0
Bank Sta=309.8,339.3
XS Rating Curve= 0 ,0
Exp/Cntr(USF)=0,0
Exp/Cntr=0.3,0.1

Type RM Length L Ch R = 1 ,11136   ,336.2,336.2,336.2
XS GIS Cut Line= 2
2284090.07288979562745.0229659962284682.34835752562840.990514254
#Sta/Elev= 30
       0 3885.01    22.4 3875.21    34.5 3868.83      67 3858.42    91.3 3847.63
    99.4 3846.33   115.6 3837.43   123.7 3835.85   135.9    3829   212.8 3797.51
   221.7 3792.28   237.2 3778.47   253.8 3767.24   257.4  3765.1   268.53762.421
   285.8 3761.46   305.13762.428   310.1 3764.83   322.3 3766.35   330.4 3765.69
   342.5 3767.04   350.6 3765.82   370.9 3770.73   411.4 3773.61   431.7 3777.08
     456  3778.4   472.2 3780.96   496.5 3781.78   528.9 3785.54     600 3803.05
#Mann= 3 ,-1,0
       0      .1       0   268.5    .045       0   305.1      .1       0
Bank Sta=268.5,305.1
XS Rating Curve= 0 ,0
Exp/Cntr(USF)=0,0
Exp/Cntr=0.3,0.1

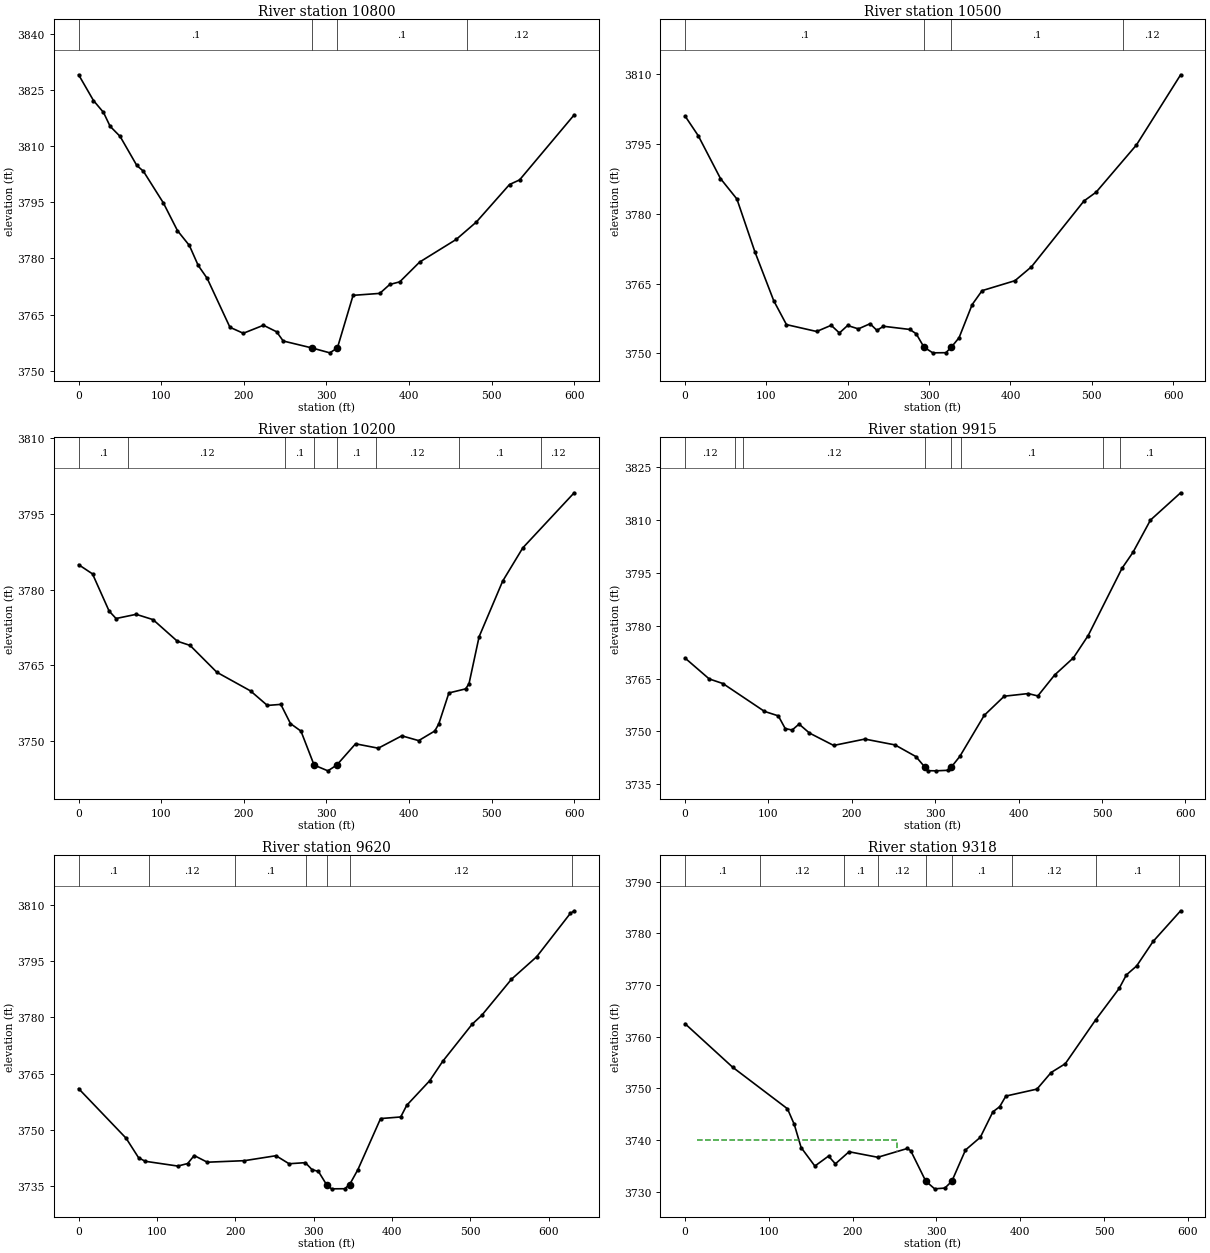
Type RM Length L Ch R = 1 ,10800   ,300.4,300.4,300.4
XS GIS Cut Line= 2
 2284138.3123695563073.627375193 2284733.8294332563146.835481594
#Sta/Elev= 30
       0 3829.01      18 3822.13    30.1 3818.97    38.1 3815.27    50.2 3812.57
    70.4 3804.83    78.4 3803.28   102.6 3794.82   119.7 3787.41   134.1 3783.46
   144.8 3778.13   155.6 3774.71   183.2 3761.64   199.4 3760.04   223.8 3762.18
   239.7 3760.44   247.7 3757.98   282.9  3756.1   304.1 3754.82   313.33756.118
   332.3 3770.16   364.6 3770.68   376.7 3773.06   388.8 3773.76   412.9 3779.04
   457.1 3785.07   481.5 3789.71   521.7 3799.73   533.9 3800.96     600 3818.31
#Mann= 4 ,-1,0
       0      .1       0   282.9    .045       0   313.3      .1       0
     470     .12       0
Bank Sta=282.9,313.3
XS Rating Curve= 0 ,0
Exp/Cntr(USF)=0,0
Exp/Cntr=0.3,0.1

Type RM Length L Ch R = 1 ,10500   ,299.6,299.6,299.6
XS GIS Cut Line= 3
2284113.66781412563273.0108202062284287.06858303563406.030588139
2284673.96473652563351.931627047
#Sta/Elev= 30
       0 3801.03    16.2  3796.8    43.5  3787.6    63.7  3783.2    85.7  3771.9
     109 3761.32   124.6  3756.2   161.7 3754.72   179.6 3756.05   189.7  3754.4
   199.8 3756.01     213 3755.28   227.4 3756.39   235.8 3754.96   243.9 3755.84
   276.2 3755.16   284.1 3754.23293.70583751.341   304.5 3750.13   320.6 3750.16
327.10573751.313   336.8 3753.38   352.9  3760.5   365.1  3763.5   405.5 3765.64
   425.8 3768.63   490.3 3782.77   505.3 3784.67   554.9 3794.83   609.2 3809.91
#Mann= 4 ,-1,0
       0      .1       0293.7058    .045       0327.1057      .1       0
  538.55     .12       0
Bank Sta=293.7058,327.1057
XS Rating Curve= 0 ,0
Exp/Cntr(USF)=0,0
Exp/Cntr=0.3,0.1

Type RM Length L Ch R = 1 ,10200   ,284.7,284.7,284.7
XS GIS Cut Line= 2
2284047.64310612563740.260814306 2284637.2527496563629.083171297
#Sta/Elev= 30
       0 3784.91    16.8 3783.09    36.9 3775.74    45.3 3774.26    69.7 3775.09
    90.1 3774.04   119.5 3769.77   134.9 3768.94   167.4 3763.62   208.1 3759.94
   228.5 3757.06   244.8 3757.27   256.5 3753.47   269.2 3751.98   285.13745.265
   301.8 3744.12   312.53745.256   335.3 3749.47   362.8  3748.6   391.3 3751.05
   411.7  3750.1   431.2    3752   436.1 3753.42   448.3 3759.53   468.6 3760.34
   472.7 3761.38   484.9 3770.66   513.4 3781.65   537.8 3788.24     600 3799.14
#Mann= 8 ,-1,0
       0      .1       0      60     .12       0     250      .1       0
   285.1    .045       0   312.5      .1       0     360     .12       0
     460      .1       0     560     .12       0
Bank Sta=285.1,312.5
XS Rating Curve= 0 ,0
Exp/Cntr(USF)=0,0
Exp/Cntr=0.3,0.1

Type RM Length L Ch R = 1 ,9915    ,294.9,294.9,294.9
XS GIS Cut Line= 3
2284240.42681522564004.9727318672284463.10852755563943.242256203
2284761.96199598563736.634810757
#Sta/Elev= 30
       0 3770.84    28.9 3764.93    45.4 3763.61    95.2 3755.71   111.8 3754.44
   120.1 3750.83   128.4 3750.41   136.7 3752.11   149.1 3749.57   178.2 3746.04
   215.6 3747.85   251.8 3746.19   276.9 3742.87   287.33739.967   290.8 3738.88
   300.5 3738.83     315 3738.98   319.53739.958   329.6 3742.95   358.8 3754.58
   382.8 3760.02   411.6 3760.77   423.1 3760.09   443.2 3766.03   465.8 3770.92
   483.5 3777.25   524.1 3796.35   537.2 3800.86   558.2 3810.03   594.4 3817.78
#Mann= 8 ,-1,0
       0     .12       0      60      .1       0      70     .12       0
   287.3    .045       0   319.5     .12       0  331.08      .1       0
  501.08     .12       0  521.08      .1       0
Bank Sta=287.3,319.5
XS Rating Curve= 0 ,0
Exp/Cntr(USF)=0,0
Exp/Cntr=0.3,0.1

Type RM Length L Ch R = 1 ,9620    ,302.1,302.1,302.1
XS GIS Cut Line= 2
2284314.82151304564267.2365022992284920.94010955564086.413529296
#Sta/Elev= 30
       0 3761.02    60.6  3747.8    76.5 3742.61    84.9 3741.66   126.6 3740.38
   139.2 3741.06   147.5 3743.19   164.2 3741.41   211.7 3741.82   251.9 3743.14
   268.6    3741   289.4 3741.29   297.8 3739.45   306.1 3738.94   316.43735.445
   322.8 3734.31   339.5 3734.34   345.93735.457   356.4 3739.41   385.4 3753.04
   411.1 3753.47   418.8 3756.58   448.1 3763.13   464.7  3768.3   502.3  3778.2
   514.8 3780.63   552.5 3790.19   584.7 3796.19   627.5 3807.71   632.5 3808.43
#Mann= 7 ,-1,0
       0      .1       0      90     .12       0     200      .1       0
     290     .12       0   316.4    .045       0   345.9     .12       0
     630      .1       0
Bank Sta=316.4,345.9
XS Rating Curve= 0 ,0
Exp/Cntr(USF)=0,0
Exp/Cntr=0.3,0.1

Type RM Length L Ch R = 1 ,9318    ,339.5,339.5,339.5
XS GIS Cut Line= 2
2284412.59038746564526.7075438792284991.57187272564405.665564673
#Sta/Elev= 30
       0 3762.52    56.8  3754.1   122.2 3746.06   130.3 3743.04   138.5 3738.55
   154.9 3734.97   171.2  3736.9   179.4  3735.4   195.7 3737.74     230 3736.67
   265.2 3738.37   269.3 3737.95   287.33732.042   297.9 3730.56   310.1 3730.71
   318.43732.034   334.7 3738.08   352.4 3740.54   367.4 3745.47   375.5 3746.46
   382.9 3748.52     420 3749.87   436.9 3753.08   453.8 3754.78     490 3763.26
   518.1 3769.35   526.7 3771.97     539 3773.71   558.6 3778.45   591.5 3784.39
#Mann= 9 ,-1,0
       0      .1       0      90     .12       0     190      .1       0
     230     .12       0   287.3    .045       0   318.4      .1       0
     390     .12       0     490      .1       0     590     .12       0
#XS Ineff= 1 ,-1
13.93412252.4536    3740
Permanent Ineff=
       F
Bank Sta=287.3,318.4
XS Rating Curve= 0 ,0
Exp/Cntr(USF)=0,0
Exp/Cntr=0.3,0.1

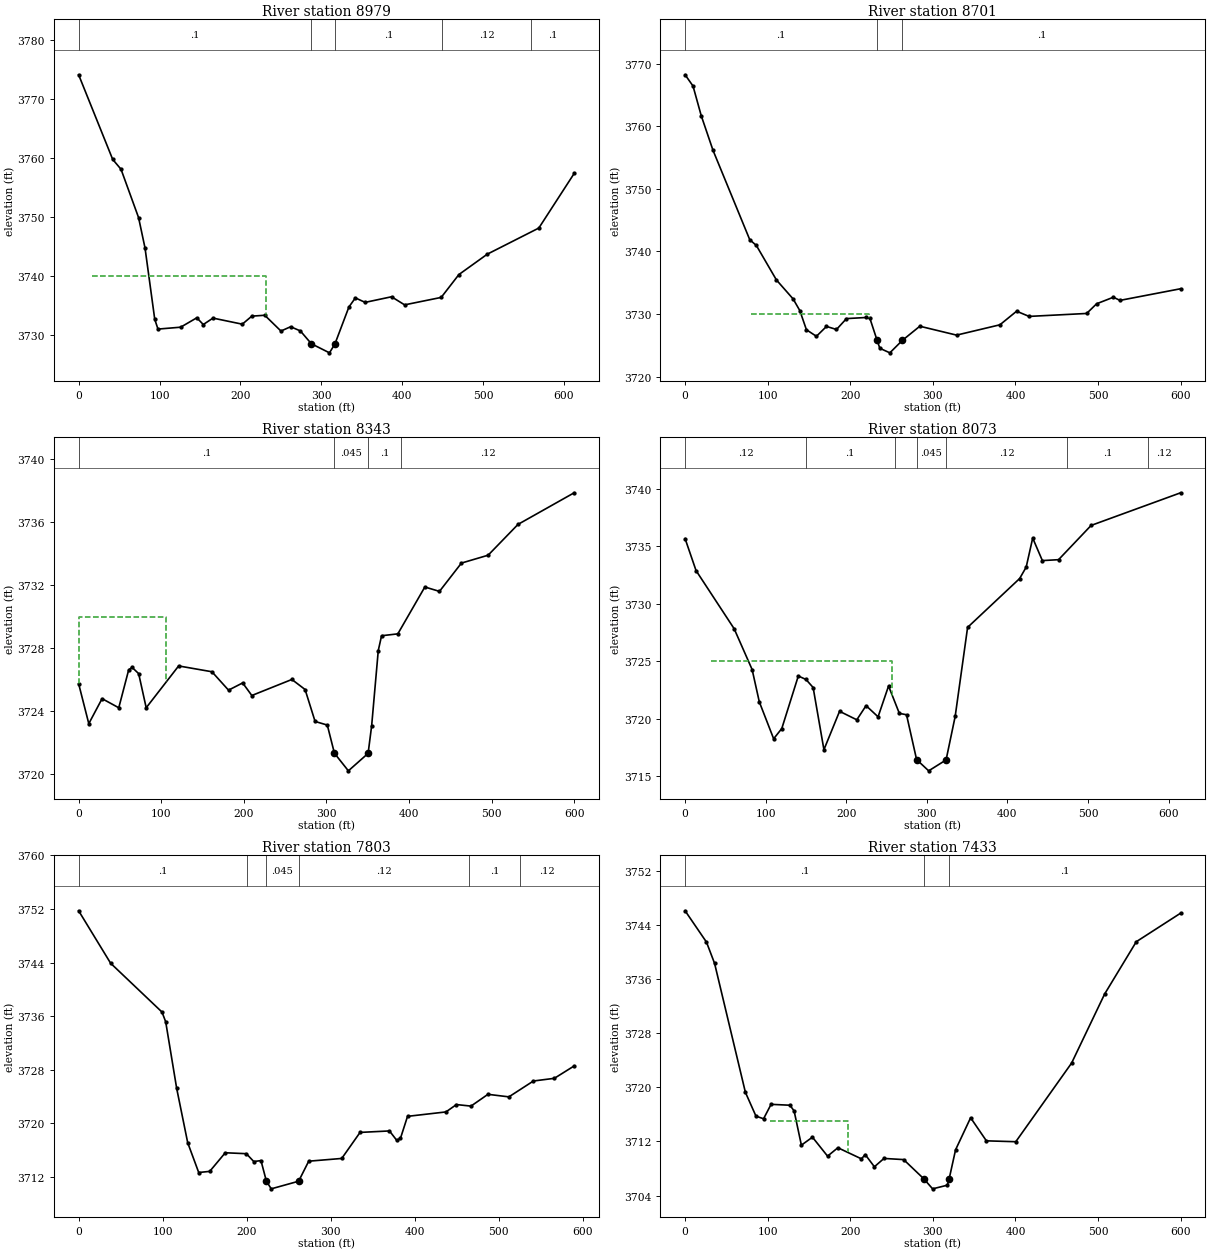
Type RM Length L Ch R = 1 ,8979    ,277.9,277.9,277.9
XS GIS Cut Line= 3
2284450.05267234 564803.602287712284829.55147465564798.821101445
2285042.17121562564703.233934285
#Sta/Elev= 30
       0 3774.04    42.1 3759.72    52.4 3758.05    74.1 3749.87    82.1 3744.71
    94.1 3732.65    98.1    3731   126.1 3731.32   146.1 3732.91   154.1 3731.77
   166.1 3732.86   202.3 3731.83   214.1 3733.19   230.1 3733.34   250.1 3730.67
   262.1  3731.4   274.1 3730.69   287.7 3728.52   310.1 3726.98   316.93728.504
   334.1 3734.73   342.1 3736.28   354.2 3735.52   386.8 3736.47     403  3735.1
   448.2 3736.36   470.1 3740.23   505.2 3743.68   568.9  3748.1   612.6 3757.34
#Mann= 5 ,-1,0
       0      .1       0   287.7    .045       0   316.9      .1       0
  449.53     .12       0  559.53      .1       0
#XS Ineff= 1 ,-1
16.41499231.6399    3740
Permanent Ineff=
       F
Bank Sta=287.7,316.9
XS Rating Curve= 0 ,0
Exp/Cntr(USF)=0,0
Exp/Cntr=0.3,0.1

Type RM Length L Ch R = 1 ,8701    ,357.9,357.9,357.9
XS GIS Cut Line= 2
2284450.65194704565101.6747249252285044.91287566565018.886146547
#Sta/Elev= 30
       0 3768.22     9.6 3766.42    19.5  3761.7    33.8 3756.15    78.3 3741.87
    86.3 3740.95   110.6 3735.44   130.8 3732.41   138.9 3730.55   146.9 3727.49
     159 3726.44   171.2 3728.02   183.3 3727.53   195.4 3729.27   219.6 3729.45
   223.7 3729.33   232.53725.785   235.8 3724.53   247.9  3723.8   263.13725.796
   284.2 3728.05   328.7 3726.63   381.2 3728.28   401.4 3730.45   416.5 3729.62
   486.2 3730.09   498.3 3731.64   518.5 3732.68   526.6 3732.18     600 3734.04
#Mann= 3 ,-1,0
       0      .1       0   232.5    .045       0   263.1      .1       0
#XS Ineff= 1 ,-1
80.27164 222.601    3730
Permanent Ineff=
       F
Bank Sta=232.5,263.1
XS Rating Curve= 0 ,0
Exp/Cntr(USF)=0,0
Exp/Cntr=0.3,0.1

Type RM Length L Ch R = 1 ,8343    ,269.6,269.6,269.6
XS GIS Cut Line= 2
2284603.97108259565258.3338567142285199.64797633565330.229880689
#Sta/Elev= 30
       0 3725.73    12.3 3723.19    28.4 3724.78    48.6  3724.2    60.6 3726.61
    64.7 3726.77    72.7 3726.37    81.8  3724.2   121.1 3726.86   161.4 3726.49
   181.5 3725.32   198.6 3725.78   209.7 3724.98   258.2    3726   274.2 3725.36
   286.3 3723.33   301.1  3723.1   309.73721.311   326.6 3720.19   350.53721.301
   354.8 3723.06   362.8 3727.84   366.8 3728.78   386.5  3728.9   419.2 3731.88
   436.9  3731.6   463.5  3733.4   495.8  3733.9     532 3735.86     600 3737.87
#Mann= 4 ,-1,0
       0      .1       0   309.7    .045       0   350.5      .1       0
     390     .12       0
#XS Ineff= 2 , 0
        106.3903    3730
Permanent Ineff=
       F       F
Bank Sta=309.7,350.5
XS Rating Curve= 0 ,0
Exp/Cntr(USF)=0,0
Exp/Cntr=0.3,0.1

Type RM Length L Ch R = 1 ,8073    ,270.4,270.4,270.4
XS GIS Cut Line= 3
2284561.53566107565411.1761333892284915.45887457565585.181642422
2285134.54239061 565559.39559076
#Sta/Elev= 30
       0 3735.67    13.6 3732.89    60.9 3727.83    83.2 3724.28    92.1 3721.47
   109.9 3718.26     120 3719.15   140.5 3723.72     150 3723.42   158.9 3722.72
   172.3 3717.31   191.7 3720.65   213.1 3719.91   224.6 3721.14   239.5 3720.17
   252.5 3722.85   265.9 3720.47   274.8 3720.35   287.3 3716.45   302.3 3715.47
   323.9 3716.42   335.2 3720.21   350.6 3727.95   415.2  3732.2   423.3 3733.19
   431.4 3735.72   443.4 3733.76   463.5 3733.84   503.9 3736.82     615 3739.66
#Mann= 7 ,-1,0
       0     .12       0     150      .1       0     260     .12       0
   287.3    .045       0   323.9     .12       0  474.39      .1       0
  574.39     .12       0
#XS Ineff= 1 ,-1
31.68168257.2277    3725
Permanent Ineff=
       F
Bank Sta=287.3,323.9
XS Rating Curve= 0 ,0
Exp/Cntr(USF)=0,0
Exp/Cntr=0.3,0.1

Type RM Length L Ch R = 1 ,7803    ,370.4,370.4,370.4
XS GIS Cut Line= 3
2284413.24828998565626.3423546232284765.75114011565780.364709754
2284962.84047605565723.937068934
#Sta/Elev= 30
       0 3751.74    38.1  3743.9    99.2 3736.61   103.6 3735.16   116.7 3725.19
   129.8 3717.09   142.9 3712.64     156 3712.81   174.5 3715.59   199.6 3715.45
   208.4 3714.28     217 3714.42   223.43711.358   229.2  3710.2   261.83711.338
   273.8 3714.33   313.1 3714.74   334.9 3718.63   369.9 3718.85   378.6 3717.44
     383 3717.75   391.4 3721.03   437.1 3721.69   449.6 3722.79   466.9 3722.56
   487.1 3724.32     512 3723.94   541.2 3726.31   566.1 3726.71   589.7 3728.56
#Mann= 6 ,-1,0
       0      .1       0     200     .12       0   223.4    .045       0
   261.8     .12       0  464.68      .1       0  524.68     .12       0
Bank Sta=223.4,261.8
XS Rating Curve= 0 ,0
Exp/Cntr(USF)=0,0
Exp/Cntr=0.3,0.1

Type RM Length L Ch R = 1 ,7433    ,357.6,357.6,357.6
XS GIS Cut Line= 2
2284388.87179997565921.3672568622284915.26632829566209.306140226
#Sta/Elev= 30
       0 3746.07    25.9 3741.44    35.7  3738.3      73 3719.26    85.8 3715.74
      95 3715.35   104.1 3717.48   126.9 3717.35     132 3716.51   140.8 3711.45
   154.2 3712.63   172.5 3709.83     185 3711.07   213.5 3709.43   218.1 3710.06
   229.2 3708.26   240.8 3709.49   264.6 3709.32   288.93706.498   299.7    3705
   317.6 3705.54   319.83706.518   327.5 3710.77   345.7  3715.5   364.8 3712.09
   400.4 3711.96     468 3723.58     508 3733.78   546.3  3741.5     600 3745.72
#Mann= 3 ,-1,0
       0      .1       0   288.9    .045       0   319.8      .1       0
#XS Ineff= 1 ,-1
102.3659197.1335    3715
Permanent Ineff=
       F
Bank Sta=288.9,319.8
XS Rating Curve= 0 ,0
Exp/Cntr(USF)=0,0
Exp/Cntr=0.3,0.1