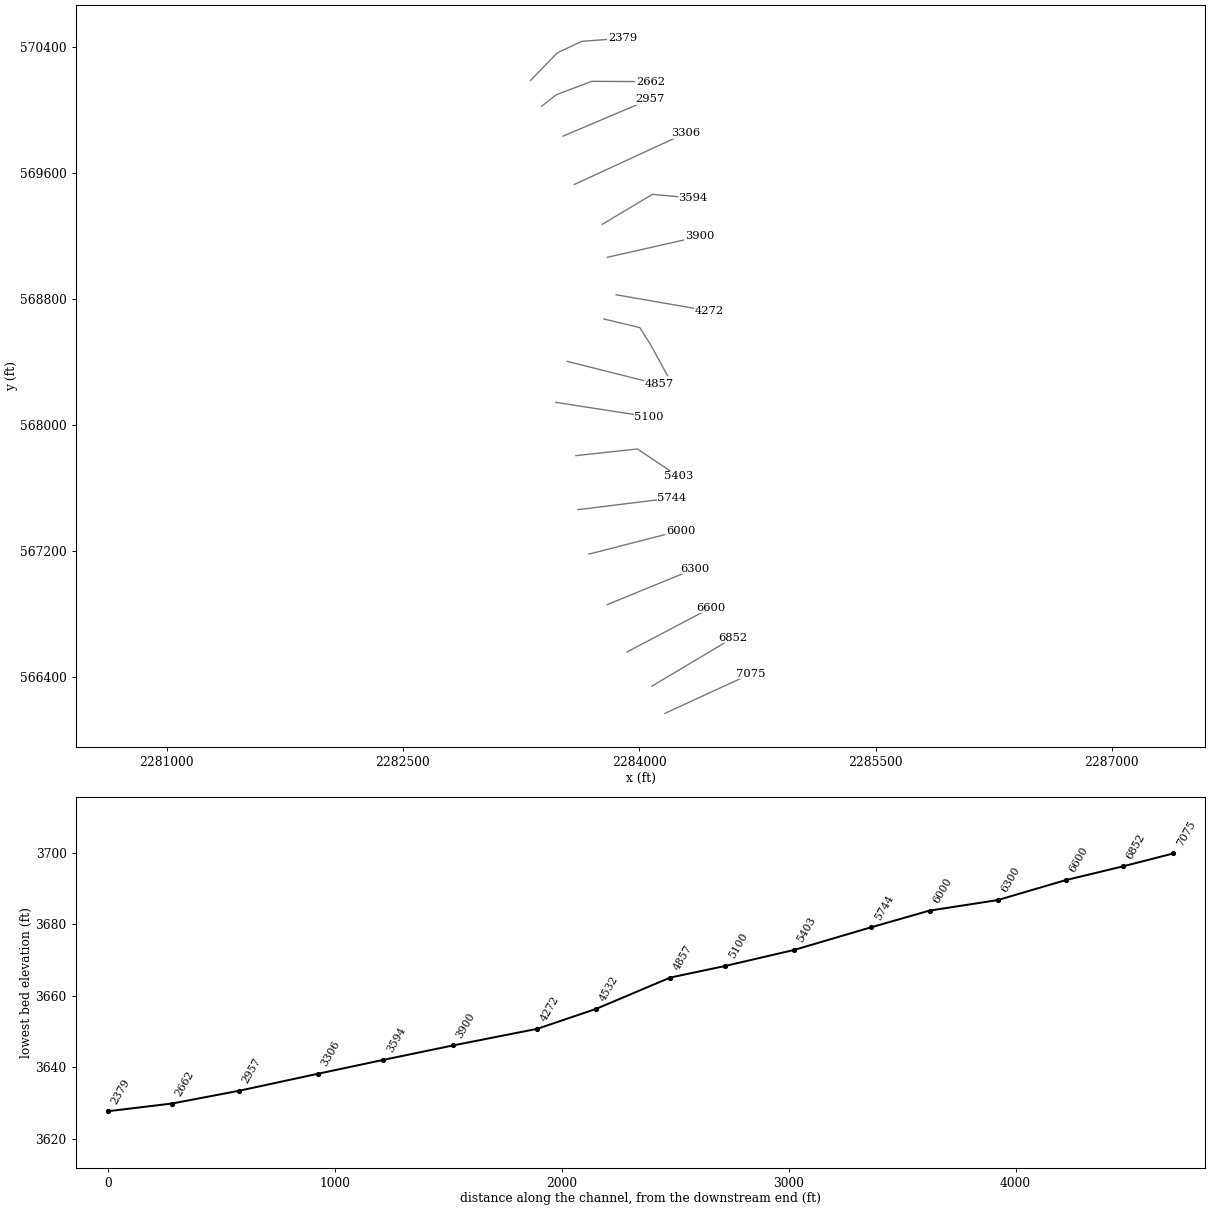
HEC-RAS study FIRSTFK.prj: FIRSTFK

--- FIRSTFK.g01 (geometry) --- (continued)

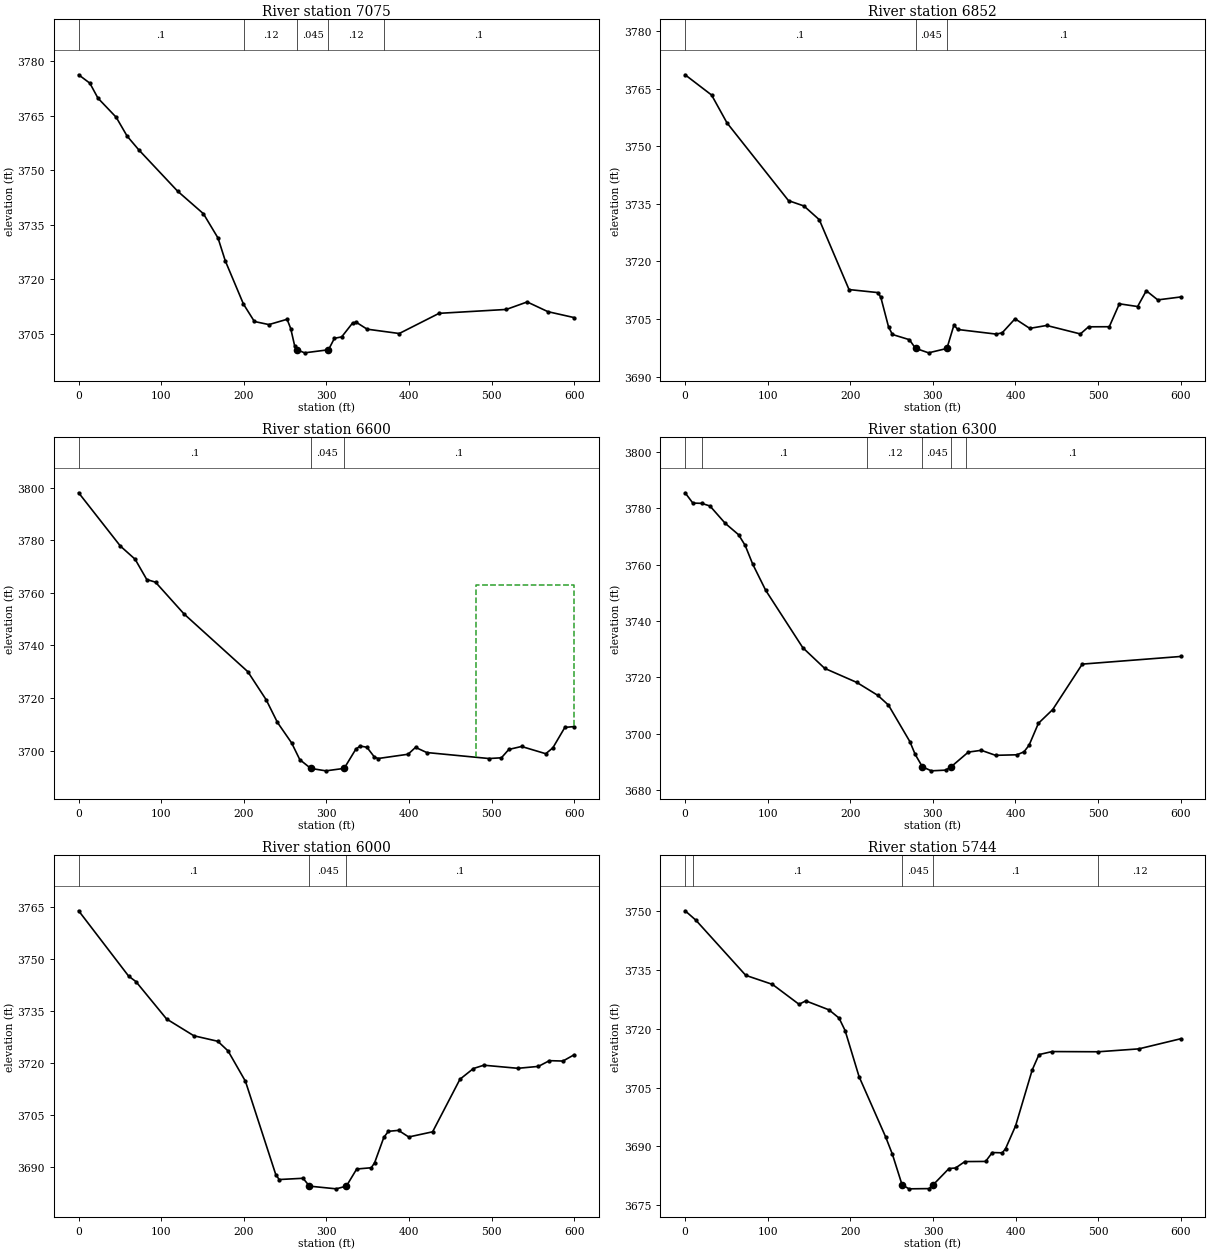
Type RM Length L Ch R = 1 ,7075    ,223,223,223
XS GIS Cut Line= 2
2284162.89311128566171.480230724 2284707.8587332566422.503080123
#Sta/Elev= 30
       0  3776.2    13.6 3773.89    23.4 3769.78    45.5 3764.52    58.7 3759.36
    72.6 3755.64   119.8 3744.24   151.1 3738.03   168.8 3731.34   177.6 3725.07
   199.6  3713.2   212.8 3708.43   230.4 3707.58   252.4 3709.04   256.8 3706.49
   261.5 3701.81   264.53700.667   273.6 3699.82   302.5 3700.66   309.7 3703.81
   318.5  3704.2   331.7 3708.01   336.1 3708.22   349.3 3706.32   388.2 3705.13
   436.4 3710.67   517.8 3711.74   543.1  3713.8   568.2 3711.13     600  3709.5
#Mann= 5 ,-1,0
       0      .1       0     200     .12       0   264.5    .045       0
   302.5     .12       0     370      .1       0
Bank Sta=264.5,302.5
XS Rating Curve= 0 ,0
Exp/Cntr(USF)=0,0
Exp/Cntr=0.3,0.1

Type RM Length L Ch R = 1 ,6852    ,251.9,251.9,251.9
XS GIS Cut Line= 2
 2284080.6138582566344.5546945572284595.94484552566651.855806668
#Sta/Elev= 30
       0 3768.61    32.1 3763.33    50.7 3756.09   125.2 3735.83   143.9 3734.44
   162.5 3730.86   198.5 3712.67   233.5 3711.88     237 3710.64   246.3 3702.97
     251 3700.97   271.5 3699.62     2793697.368   294.8 3696.19     3173697.333
   325.5 3703.41   330.2 3702.27   376.7 3701.07   383.9  3701.4   399.5 3705.06
   417.3 3702.56   437.8 3703.32   478.6 3701.11   488.5 3702.97   513.6 3702.99
   525.8 3708.96   547.9 3708.25   558.4 3712.36   572.3 3709.98     600 3710.74
#Mann= 3 ,-1,0
       0      .1       0     279    .045       0     317      .1       0
Bank Sta=279,317
XS Rating Curve= 0 ,0
Exp/Cntr(USF)=0,0
Exp/Cntr=0.3,0.1

Type RM Length L Ch R = 1 ,6600    ,300,300,300
XS GIS Cut Line= 2
2283923.18728045566561.8094829762284454.18110527566841.175833839
#Sta/Elev= 30
       0 3798.06    50.6 3777.78    68.4 3772.79    82.5 3765.08    93.1 3764.07
   127.6    3752   204.8 3730.06   227.1 3719.35   240.7 3710.76   257.9 3702.95
   267.8 3696.59   281.13693.255   299.4 3692.34   321.53693.271   335.6 3700.57
   340.9 3701.79   349.1 3701.29   358.2 3697.55   362.7 3697.03   398.9 3698.65
   407.9 3701.26   421.5  3699.3   496.9 3697.02   511.9  3697.3   520.9 3700.48
   536.3  3701.6   565.6 3698.85   574.2 3701.09   588.7 3708.85     600 3709.17
#Mann= 3 ,-1,0
       0      .1       0   281.1    .045       0   321.5      .1       0
#XS Ineff= 2 , 0
                        481.3632            3763
Permanent Ineff=
       F       F
Bank Sta=281.1,321.5
XS Rating Curve= 0 ,0
Exp/Cntr(USF)=0,0
Exp/Cntr=0.3,0.1

Type RM Length L Ch R = 1 ,6300    ,300,300,300
XS GIS Cut Line= 2
2283796.36033064566861.5997622212284351.47269098567089.306300124
#Sta/Elev= 30
       0 3785.49     9.4 3781.83      20 3781.74    30.1  3780.8    48.6 3774.64
    64.7 3770.61    72.7 3766.82    81.9 3760.13    97.6 3750.85   142.5 3730.48
     169 3723.14     208 3718.13   233.3 3713.56   246.2 3710.11   272.2 3697.11
   278.5 3692.64   287.33688.181   298.1 3686.75   315.4    3687     3223688.169
   342.9  3693.4   358.6 3694.04   375.9 3692.26   401.9 3692.45   410.4 3693.52
   416.5 3695.86   427.8 3703.63   445.1 3708.51   480.9 3724.65     600 3727.36
#Mann= 6 ,-1,0
       0     .07       0      20      .1       0     220     .12       0
   287.3    .045       0     322     .12       0     340      .1       0
Bank Sta=287.3,322
XS Rating Curve= 0 ,0
Exp/Cntr(USF)=0,0
Exp/Cntr=0.3,0.1

Type RM Length L Ch R = 1 ,6000    ,256.4,256.4,256.4
XS GIS Cut Line= 2
2283680.99050415567182.5459112412284262.15204859567331.714471126
#Sta/Elev= 30
       0 3763.86    60.6 3745.03    69.4 3743.47   106.5 3732.71   139.5 3727.88
   168.5 3726.29   180.9 3723.52     202 3714.76   238.7 3687.91   242.8 3686.49
   271.7 3686.85   279.53684.587   311.9 3683.81   324.23684.596   336.7 3689.52
   354.3 3689.88   358.4 3691.33   369.5  3698.6     375 3700.37   387.3 3700.64
   399.7 3698.74   428.6 3700.23   461.7 3715.36     478 3718.45   490.6  3719.4
   531.9 3718.51   556.7 3719.06     570 3720.71   586.4  3720.6     600 3722.41
#Mann= 3 ,-1,0
       0      .1       0   279.5    .045       0   324.2      .1       0
Bank Sta=279.5,324.2
XS Rating Curve= 0 ,0
Exp/Cntr(USF)=0,0
Exp/Cntr=0.3,0.1

Type RM Length L Ch R = 1 ,5744    ,340.3,340.3,340.3
XS GIS Cut Line= 2
2283611.28432924567464.7544771982284206.38561198567537.982783814
#Sta/Elev= 30
       0 3750.18      13 3747.79    73.4 3733.69   105.7 3731.38   137.9 3726.29
     146 3727.17   174.2 3724.87   186.3 3722.77   193.6 3719.59   210.5 3707.82
   242.7  3692.4   250.8 3688.01   262.53680.206   270.9 3679.16   295.1 3679.22
   300.23680.203   319.3 3684.35   327.3 3684.49   338.5 3686.12   363.6 3686.16
   371.7 3688.43   383.8 3688.36   387.8 3689.44   399.9 3695.25     420 3709.53
   428.2 3713.45   444.2 3714.22     500 3714.17     549 3714.91   599.6 3717.49
#Mann= 5 ,-1,0
       0     .06       0      10      .1       0   262.5    .045       0
   300.2      .1       0     500     .12       0
Bank Sta=262.5,300.2
XS Rating Curve= 0 ,0
Exp/Cntr(USF)=0,0
Exp/Cntr=0.3,0.1

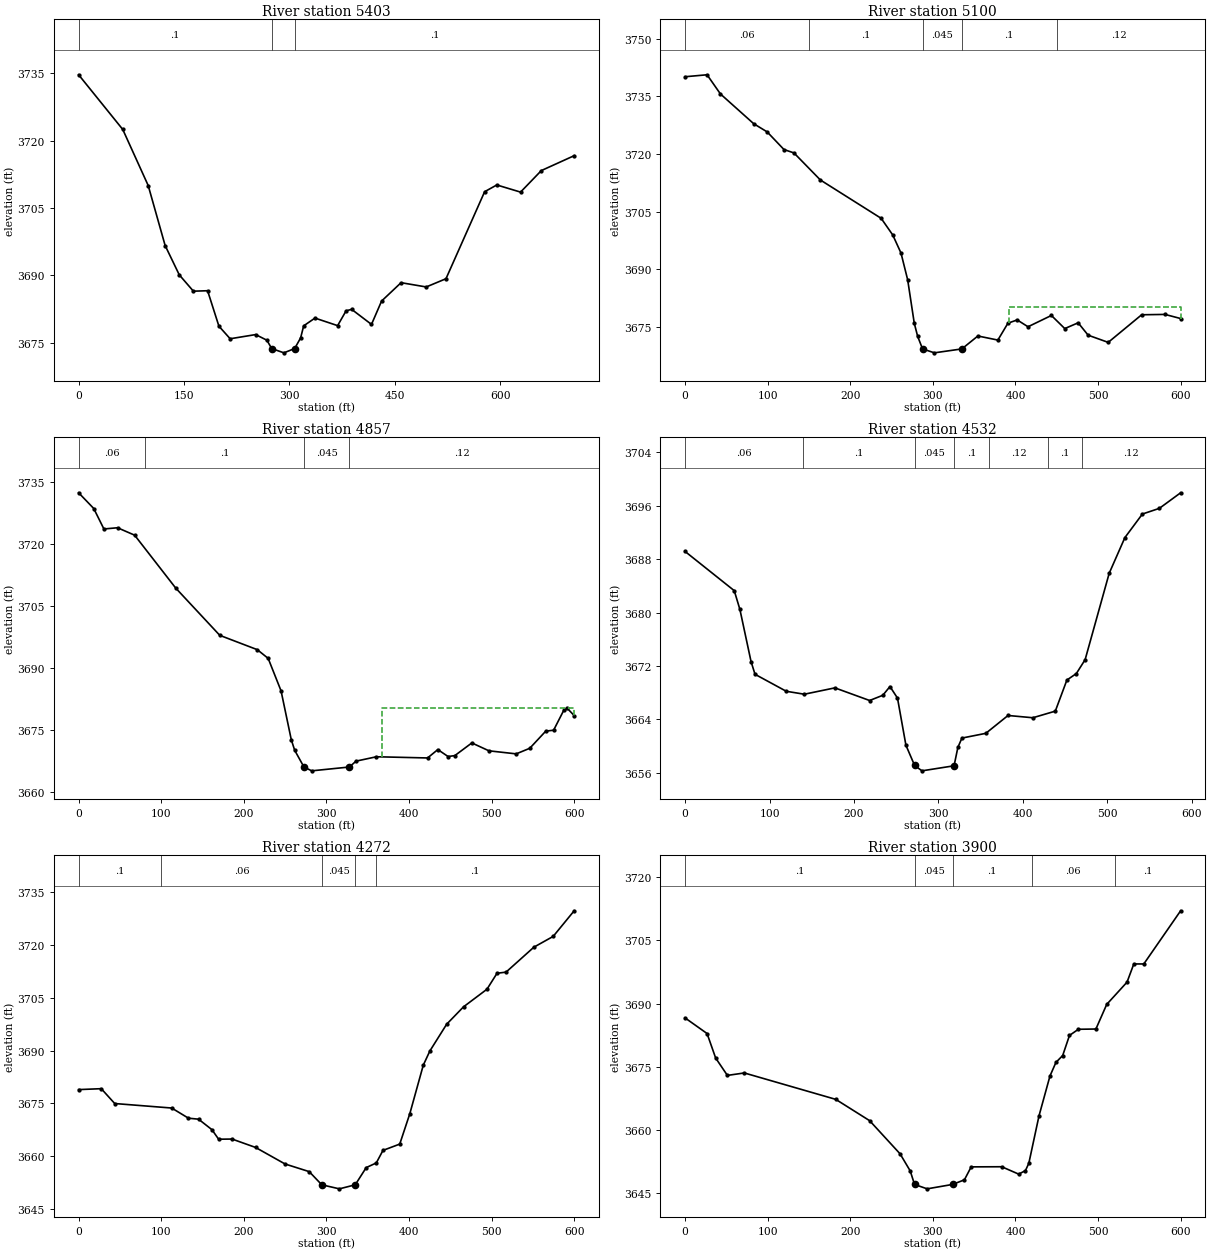
Type RM Length L Ch R = 1 ,5403    ,303.4,303.4,303.4
XS GIS Cut Line= 3
2283597.77359819567807.6071525642283988.69578353567849.785817271
2284247.54867997567675.705898916
#Sta/Elev= 30
       0 3734.63    62.8 3722.47      99    3710   123.1 3696.66   143.2 3690.14
   163.3 3686.51   183.5 3686.61   199.6 3678.73   215.6 3675.93   251.9 3676.86
   267.9  3675.6   274.73673.749   292.1  3672.8   307.43673.759   315.9 3676.13
   320.2  3678.8   336.3 3680.53   368.5 3678.85   380.6 3682.15   388.5 3682.47
   416.7 3679.12   431.1 3684.32   458.8  3688.4   494.6 3687.45   522.7 3689.28
   577.7 3708.63     595 3710.13   628.8 3708.54   658.4 3713.33   705.1 3716.64
#Mann= 3 ,-1,0
       0      .1       0   274.7    .045       0   307.4      .1       0
Bank Sta=274.7,307.4
XS Rating Curve= 0 ,0
Exp/Cntr(USF)=0,0
Exp/Cntr=0.3,0.1

Type RM Length L Ch R = 1 ,5100    ,243.1,243.1,243.1
XS GIS Cut Line= 2
2283469.89821167568145.7960364662284062.83173841568053.981915157
#Sta/Elev= 30
       0 3740.12    26.6 3740.63    42.8 3735.64    83.1  3727.9    99.4 3725.77
   119.7 3721.19   131.8 3720.31   163.8 3713.27   237.4  3703.3   251.4 3698.98
   261.4 3694.28   269.5  3687.3   277.5    3676   281.6 3672.59   287.5 3669.35
   301.8 3668.32   335.13669.341   354.5  3672.7   378.7 3671.64   390.9 3676.03
   402.1 3676.88   415.2  3675.1   443.5 3678.04   459.7 3674.63   475.9 3676.13
     488 3672.91   512.3 3671.04   552.8 3678.22   581.1 3678.31     600 3677.24
#Mann= 5 ,-1,0
       0     .06       0     150      .1       0   287.5    .045       0
   335.1      .1       0     450     .12       0
#XS Ineff= 2 , 0
                        392.7805         3680.22
Permanent Ineff=
       F       F
Bank Sta=287.5,335.1
XS Rating Curve= 0 ,0
Exp/Cntr(USF)=0,0
Exp/Cntr=0.3,0.1

Type RM Length L Ch R = 1 ,4857    ,325.4,325.4,325.4
XS GIS Cut Line= 2
2283542.46942903568406.0655742972284124.29710254568259.516748546
#Sta/Elev= 30
       0 3732.41    18.3  3728.6    30.6 3723.64    47.1 3723.94    67.8 3722.14
   117.5 3709.34   170.9 3697.88   216.3 3694.41   229.5  3692.3   245.1 3684.43
   257.5 3672.58   261.6 3670.04   272.83665.994   282.2 3665.06   327.83665.987
   335.9 3667.41   360.6 3668.47   422.5 3668.18   434.9 3670.21   447.3 3668.53
   455.5 3668.75   476.1 3671.82   496.8 3669.91   529.8 3669.17   546.2 3670.52
   565.6 3674.68   575.1  3674.9   587.5 3679.76   591.6 3680.22     600 3678.44
#Mann= 4 ,-1,0
       0     .06       0      80      .1       0   272.8    .045       0
   327.8     .12       0
#XS Ineff= 2 , 0
                        367.8317         3680.22
Permanent Ineff=
       F       F
Bank Sta=272.8,327.8
XS Rating Curve= 0 ,0
Exp/Cntr(USF)=0,0
Exp/Cntr=0.3,0.1

Type RM Length L Ch R = 1 ,4532    ,259.7,259.7,259.7
XS GIS Cut Line= 4
2283775.64286844568674.8260030882284003.41893765568620.297549793
2284070.49108422568513.9636588932284179.56717786568315.064400981
#Sta/Elev= 30
       0 3689.13    58.2 3683.27    64.9 3680.46    78.1 3672.66    82.8 3670.76
   119.8 3668.22   141.2 3667.78   177.4 3668.73   218.5 3666.84   234.1 3667.62
   242.6 3668.93   251.5  3667.2   261.5 3660.15   271.8 3657.12   280.5 3656.32
   318.53657.077     323 3659.82   327.8 3661.22   356.1 3661.93   382.4  3664.6
   411.8 3664.26   438.4 3665.25   452.1  3669.9   463.3 3670.87   473.7 3672.95
   502.2 3685.87   520.8 3691.21   541.5 3694.73   561.6 3695.58   586.8 3697.91
#Mann= 7 ,-1,0
       0     .06       0     140      .1       0   271.8    .045       0
   318.5      .1       0  359.93     .12       0  429.93      .1       0
  469.93     .12       0
Bank Sta=271.8,318.5
XS Rating Curve= 0 ,0
Exp/Cntr(USF)=0,0
Exp/Cntr=0.3,0.1

Type RM Length L Ch R = 1 ,4272    ,371.8,371.8,371.8
XS GIS Cut Line= 2
 2283853.1433802568828.8343471022284444.23323269568725.815968712
#Sta/Elev= 30
       0 3678.94    27.4  3679.2    43.7 3674.98   112.7  3673.7     133 3670.81
   145.2 3670.53   161.4 3667.55   169.5 3664.84   185.8 3664.88   214.2  3662.5
     250 3657.79   279.2 3655.62   294.4 3651.88   315.7 3650.73   334.93651.876
   348.2 3656.77   360.4 3658.09   368.5 3661.66   388.8 3663.45     401 3672.09
   417.3 3685.88   425.3 3689.93   445.6 3697.52     466 3702.46   494.4 3707.47
   506.6 3712.01   517.5 3712.33   551.2 3719.42   574.6 3722.49     600 3729.77
#Mann= 5 ,-1,0
       0      .1       0     100     .06       0   294.4    .045       0
   334.9     .06       0     360      .1       0
Bank Sta=294.4,334.9
XS Rating Curve= 0 ,0
Exp/Cntr(USF)=0,0
Exp/Cntr=0.3,0.1

Type RM Length L Ch R = 1 ,3900    ,306.3,306.3,306.3
XS GIS Cut Line= 2
2283798.23657216569066.867949848 2284383.5050484569199.007310791
#Sta/Elev= 30
       0  3686.6    26.6  3682.9      37 3677.09    51.2 3672.97    71.7 3673.55
   182.4 3667.29   223.4 3662.24   260.3 3654.37   272.6 3650.31   277.83647.112
   293.1 3646.07   323.93647.117   338.2 3648.21   346.4 3651.28   383.4 3651.31
   403.9 3649.56   412.1  3650.4   416.2 3652.14   428.5 3663.37   441.8 3672.84
     449 3676.05   457.2 3677.69   465.4 3682.45   476.2 3683.91   497.4 3683.97
   510.5 3689.81   535.1 3695.09   543.3  3699.4   555.4  3699.4     600 3712.01
#Mann= 5 ,-1,0
       0      .1       0   277.8    .045       0   323.9      .1       0
     420     .06       0     520      .1       0
#XS Ineff= 2 , 0
                        367.5393            3650
Permanent Ineff=
       F       F
Bank Sta=277.8,323.9
XS Rating Curve= 0 ,0
Exp/Cntr(USF)=0,0
Exp/Cntr=0.3,0.1

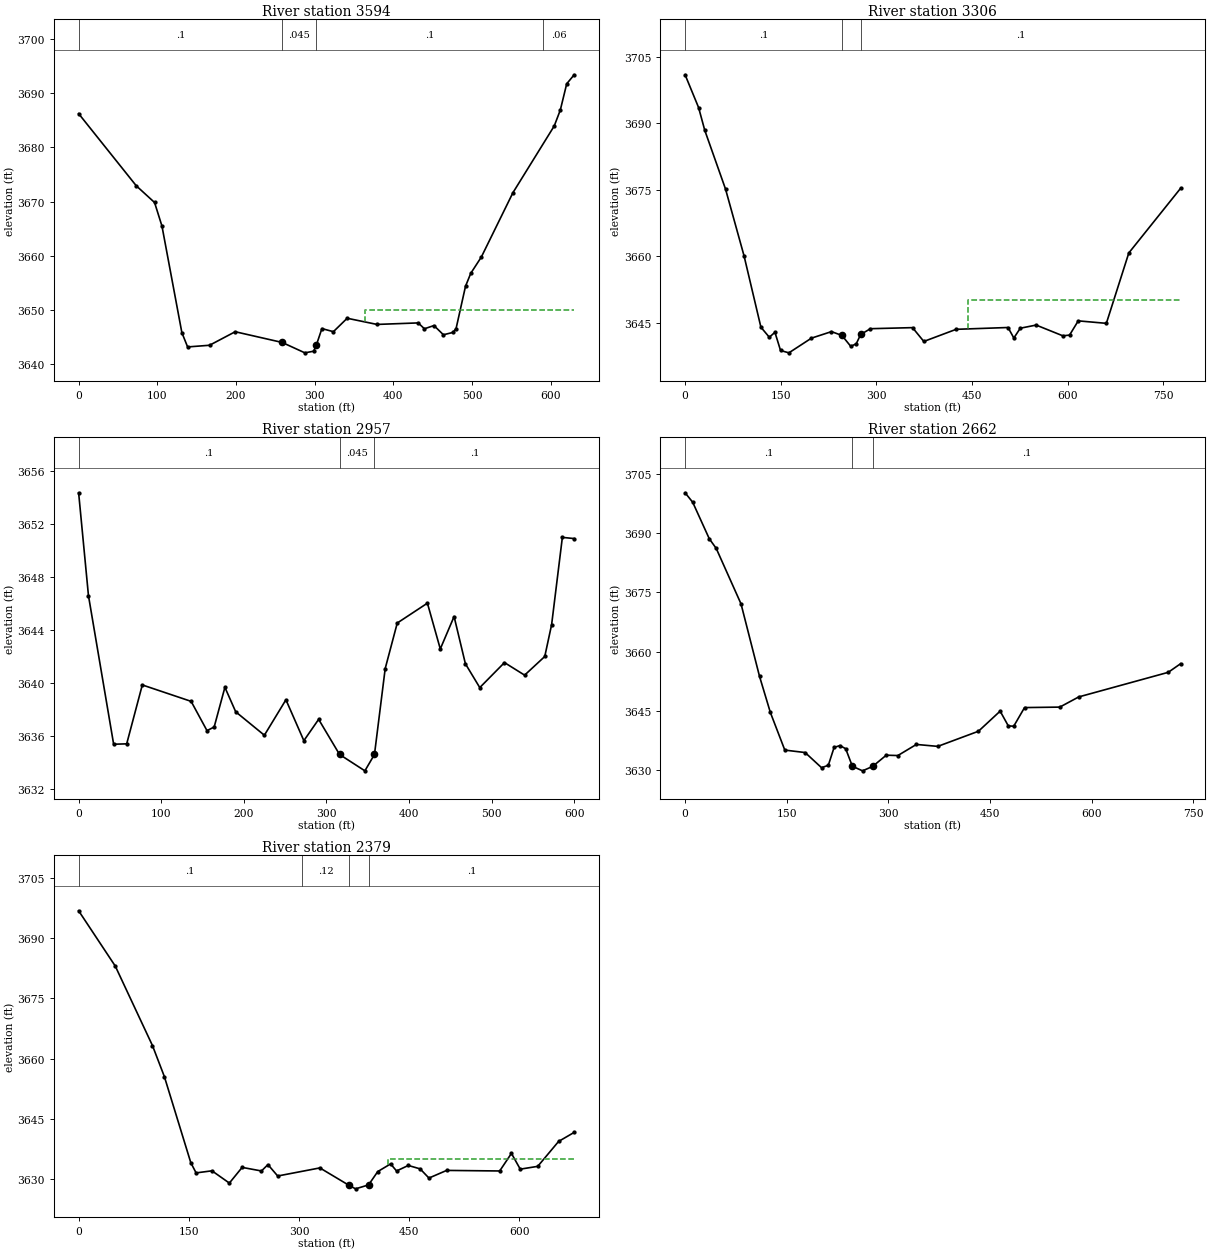
Type RM Length L Ch R = 1 ,3594    ,287.8,287.8,287.8
XS GIS Cut Line= 3
2283765.26391306569276.1728402882284083.57833233569466.060958952
2284341.71354064569442.623514263
#Sta/Elev= 30
       0 3686.24    73.3  3672.9    96.5 3669.82   105.9 3665.47   131.2 3645.78
   138.5 3643.13   166.4 3643.44     199 3645.94   258.7 3643.96   287.5 3642.04
   298.7 3642.34   302.1 3643.47   309.2 3646.52   323.8 3645.95   341.3 3648.43
   379.2 3647.29   431.5 3647.57   439.5 3646.49   451.6 3647.08   463.6 3645.38
   475.7 3645.81   479.7 3646.52   491.7 3654.34   498.4 3656.74   511.8 3659.74
     552 3671.64   604.5 3683.97   612.2 3686.91   620.3 3691.75   629.8 3693.42
#Mann= 4 ,-1,0
       0      .1       0   258.7    .045       0   302.1      .1       0
  590.65     .06       0
#XS Ineff= 2 , 0
                        364.0627            3650
Permanent Ineff=
       F       F
Bank Sta=258.7,302.1
XS Rating Curve= 0 ,0
Exp/Cntr(USF)=0,0
Exp/Cntr=0.3,0.1

Type RM Length L Ch R = 1 ,3306    ,349.2,349.2,349.2
XS GIS Cut Line= 2
  2283588.236474569528.9912983152284293.94561364569854.509238854
#Sta/Elev= 30
       0 3700.94    21.2 3693.53    30.8 3688.42    63.4 3675.14    92.4 3660.09
   118.9 3643.95   132.1 3641.68   140.9  3642.8   149.7 3638.69   162.8 3638.16
   198.2 3641.48   229.6 3642.95   245.93642.094   259.8 3639.63   268.4  3640.2
   275.4 3642.31   290.7 3643.61   356.7 3643.85   374.4 3640.73   425.1 3643.47
   506.5 3643.88   515.6 3641.51   525.7 3643.72   550.6 3644.43   592.5    3642
     603 3642.17   616.6 3645.38   660.7 3644.82   695.9 3660.71   777.2 3675.32
#Mann= 3 ,-1,0
       0      .1       0   245.9    .045       0   275.4      .1       0
#XS Ineff= 2 , 0
                        443.6429            3650
Permanent Ineff=
       F       F
Bank Sta=245.9,275.4
XS Rating Curve= 0 ,0
Exp/Cntr(USF)=0,0
Exp/Cntr=0.3,0.1

Type RM Length L Ch R = 1 ,2957    ,294.7,294.7,294.7
XS GIS Cut Line= 2
2283517.19562979569835.8834074092284069.32187965570070.737839388
#Sta/Elev= 30
       0 3654.39    11.9 3646.62    42.4 3635.39    58.2 3635.42    77.1 3639.87
   136.2 3638.63   155.4 3636.42   164.1 3636.69   177.1 3639.69   190.2 3637.84
   224.9 3636.07     251 3638.75   272.7 3635.66   290.6 3637.27   315.93634.619
   346.6 3633.38   358.23634.618   371.2 3641.11   385.8 3644.55   422.3 3646.05
   437.9 3642.59   454.6 3645.04   468.3 3641.47   485.7 3639.67   515.6 3641.56
     540 3640.61   564.4 3642.02   572.7 3644.43   585.7 3651.02     600 3650.93
#Mann= 3 ,-1,0
       0      .1       0   315.9    .045       0   358.2      .1       0
Bank Sta=315.9,358.2
XS Rating Curve= 0 ,0
Exp/Cntr(USF)=0,0
Exp/Cntr=0.3,0.1

Type RM Length L Ch R = 1 ,2662    ,282.5,282.5,282.5
XS GIS Cut Line= 4
 2283380.0306126570025.5901550142283473.62301904570098.714955969
2283698.94123962570183.6476658162284070.44652219570181.481981775
#Sta/Elev= 30
       0 3700.19    11.2  3697.8    35.7 3688.55    45.9 3686.12    82.5 3672.08
   109.8 3653.73   125.8 3644.59   147.1 3635.07   177.1 3634.45   201.3 3630.62
   211.3 3631.22   219.8 3635.73   228.4 3636.22   236.9 3635.42   246.8 3630.98
   261.8 3629.82   276.7 3630.94   296.8 3633.78   313.9 3633.69   341.2  3636.5
   372.8 3636.01   432.8 3639.84   464.8 3644.93   476.8 3641.21   484.8  3641.1
   500.8 3645.83   552.8 3645.95   580.8 3648.53   712.8 3654.75   731.1 3656.94
#Mann= 3 ,0,0
       0      .1       0   246.8    .045       0   276.7      .1       0
Bank Sta=246.8,276.7
XS Rating Curve= 0 ,0
Exp/Cntr(USF)=0,0
Exp/Cntr=0.3,0.1

Type RM Length L Ch R = 1 ,2379    ,251.5,251.5,251.5
XS GIS Cut Line= 4
2283309.84396423570189.3939916052283479.59822282570364.413109772
2283636.00006636570437.7264739332283893.39121906570456.515909729
#Sta/Elev= 30
       0 3696.76    49.9 3683.01   100.5 3663.27   116.7 3655.56   152.7 3634.16
   159.9 3631.62   181.5 3632.14   205.2 3629.09   222.6 3632.99   248.9  3632.1
   257.7 3633.68     271 3630.85   328.4 3632.86   368.1 3628.53   368.2 3628.53
     377 3627.66   394.7 3628.64   407.2 3631.95   424.7 3633.86   432.8  3632.1
   448.8 3633.47   464.9 3632.62   476.9 3630.34     501 3632.24   573.2  3632.1
   589.2 3636.47   601.2 3632.55     625 3633.25   653.4 3639.44   674.6 3641.69
#Mann= 4 ,-1,0
       0      .1       0  303.82     .12       0   368.2    .045       0
   394.7      .1       0
#XS Ineff= 2 , 0
                        421.6822            3635
Permanent Ineff=
       F       F
Bank Sta=368.1,394.7
XS Rating Curve= 0 ,0
Exp/Cntr(USF)=0,0
Exp/Cntr=0.3,0.1