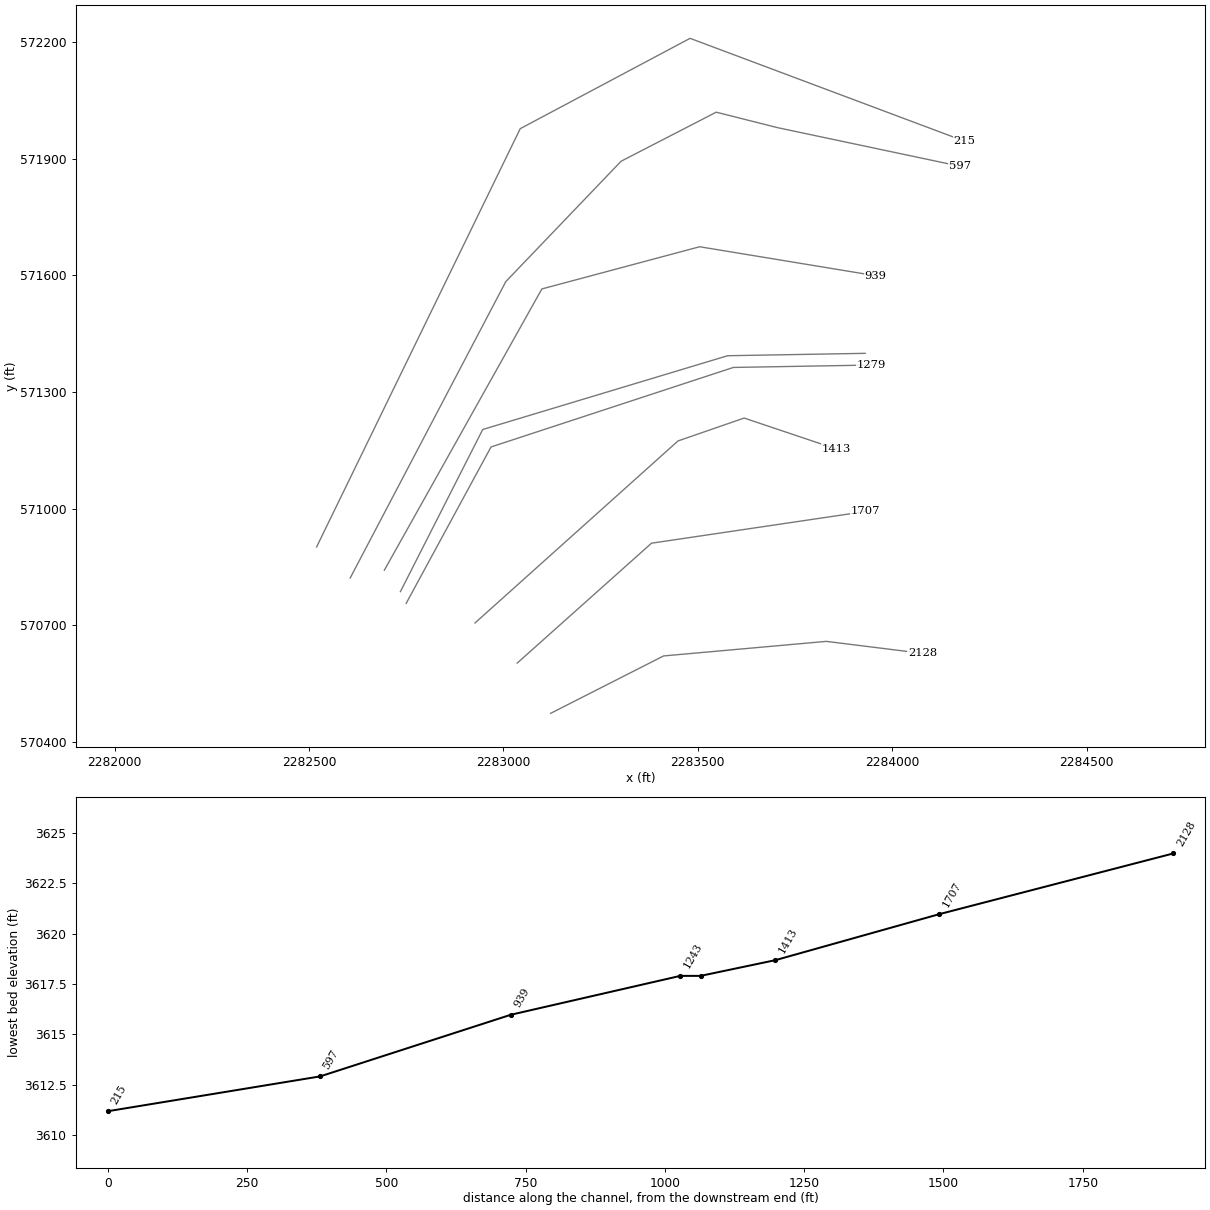
HEC-RAS study FIRSTFK.prj: FIRSTFK

--- FIRSTFK.g01 (geometry) --- (continued)

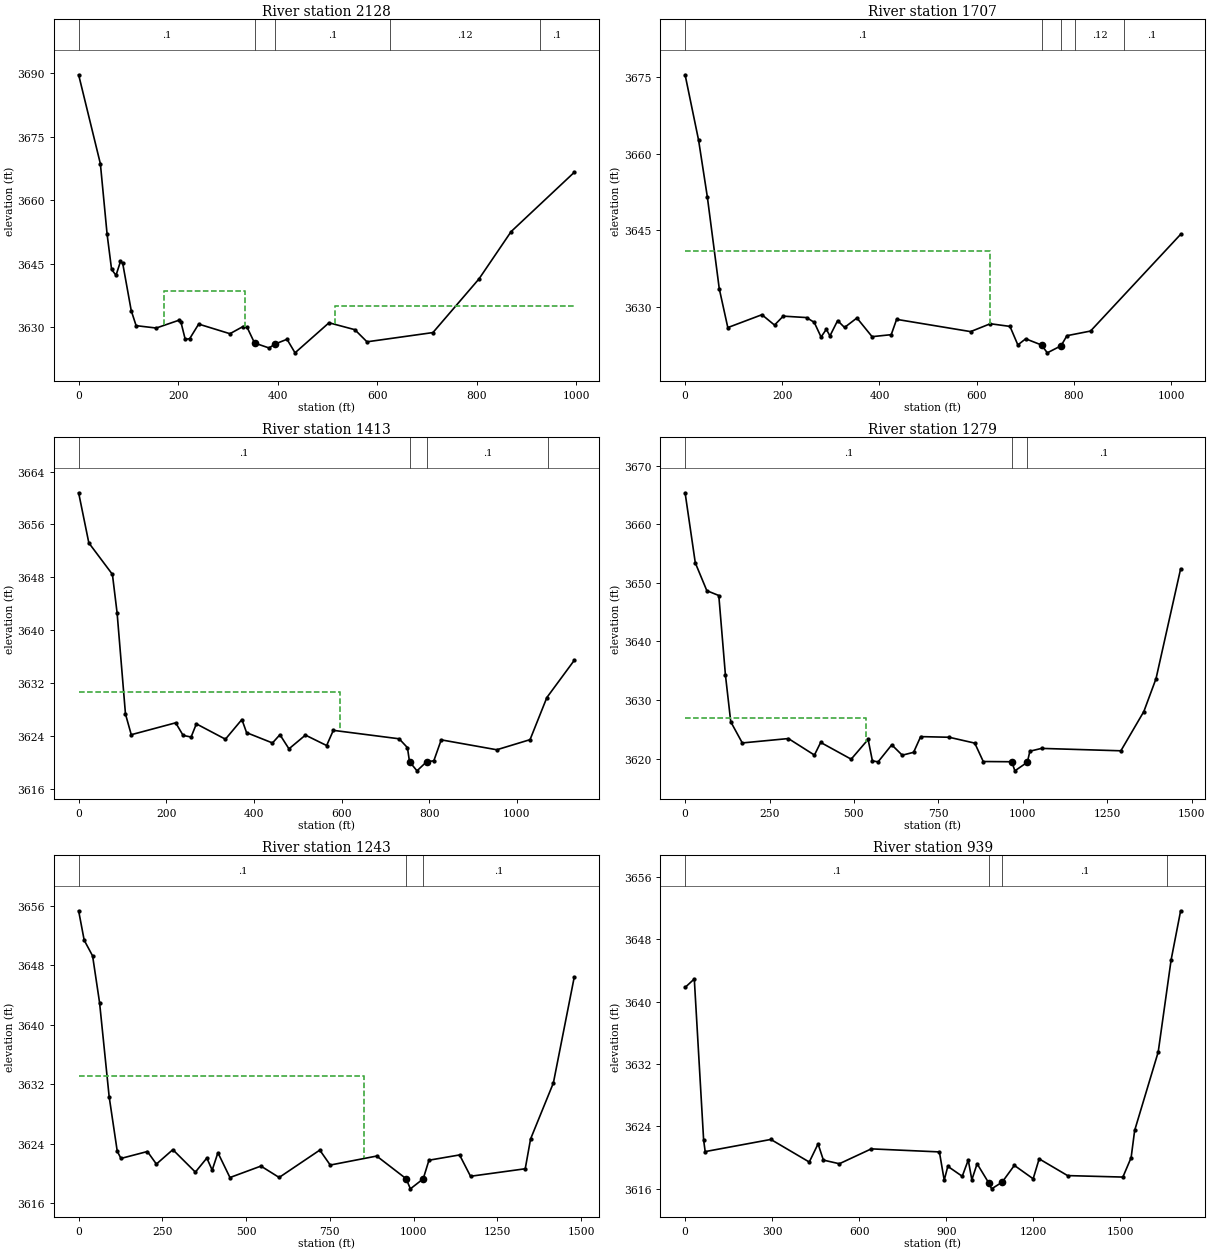
Type RM Length L Ch R = 1 ,2128    ,420.8,420.8,420.8
XS GIS Cut Line= 4
2283121.20821141570473.2786212882283411.72031635570620.995167293
  2283830.421085570658.4664423092284077.92281127570627.651753328
#Sta/Elev= 30
       0 3689.56    43.7 3668.57    57.2 3651.96    66.2 3643.67    75.1 3642.27
    84.1 3645.54    88.6 3645.07   105.7 3633.94   115.5  3630.4   155.9 3629.84
   200.8 3631.65   205.3 3631.37   214.2 3627.16   223.2 3627.34   241.2 3630.77
     304  3628.5   330.4  3630.2   338.4 3630.04   353.53626.305   382.6 3625.14
   394.6 3626.06   418.7 3627.19   434.8 3623.99   503.1 3631.08     555 3629.45
   579.4 3626.59   711.9 3628.77   804.5 3641.43     869 3652.58   995.7 3666.54
#Mann= 5 ,-1,0
       0      .1       0   353.5    .045       0   394.6      .1       0
  625.91     .12       0  926.28      .1       0
#XS Ineff= 2 ,-1
  171.28  333.52 3638.57515.7087 995.697    3635
Permanent Ineff=
       F       F
Bank Sta=353.5,394.6
XS Rating Curve= 0 ,0
Exp/Cntr(USF)=0,0
Exp/Cntr=0.3,0.1

Type RM Length L Ch R = 1 ,1707    ,293.6,293.6,293.6
XS GIS Cut Line= 3
2283035.42684792570602.6647247372283380.76578482570910.990252194
2283931.64799498570992.560219465
#Sta/Elev= 30
       0 3675.45    27.8 3662.62    45.8  3651.5    70.3 3633.54    87.9 3625.92
   158.1 3628.44     184 3626.41     202 3628.16     250 3627.88   265.8 3626.94
   279.8 3624.07   290.6 3625.58   298.1 3624.29   313.9 3627.29   328.1 3625.94
   353.6  3627.8   384.8 3624.14   424.2 3624.53   435.3 3627.53   587.6 3625.13
   628.1 3626.67   668.6 3626.15   684.8 3622.52   700.9 3623.72   733.53622.506
   745.4 3620.97   773.7 3622.35   785.8 3624.33   834.4 3625.24  1019.8 3644.19
#Mann= 5 ,-1,0
       0      .1       0   733.5    .045       0   773.7      .1       0
  802.95     .12       0  902.95      .1       0
#XS Ineff= 2 , 0
          627.47 3640.83
Permanent Ineff=
       F       F
Bank Sta=733.5,773.7
XS Rating Curve= 0 ,0
Exp/Cntr(USF)=0,0
Exp/Cntr=0.3,0.1

Type RM Length L Ch R = 1 ,1413    ,134.3,134.3,134.3
XS GIS Cut Line= 4
2282926.79843885570705.7861756842283448.84679896571173.946837409
 2283618.9810244571232.839453908 2283855.5845516571153.364734832
#Sta/Elev= 30
       0 3660.78    23.3 3653.19    77.1 3648.43    87.8 3642.59   106.9 3627.29
   120.1 3624.16   221.5 3625.96   238.5 3624.05   256.7 3623.81   268.7  3625.8
     335 3623.48   372.6 3626.46   383.3 3624.47   442.4 3622.91   459.4 3624.16
     480 3622.02   517.6  3624.1     566 3622.52   581.2 3624.82   731.5 3623.54
   750.4  3622.2   755.13620.074   772.2 3618.69   794.13620.064   810.6 3620.21
   827.5 3623.38   954.3 3621.88  1030.2 3623.41  1068.6 3629.79  1130.9  3635.4
#Mann= 4 ,-1,0
       0      .1       0   755.1    .045       0   794.1      .1       0
 1071.26     .12       0
#XS Ineff= 2 , 0
          596.19 3630.57
Permanent Ineff=
       F       F
Bank Sta=755.1,794.1
XS Rating Curve= 0 ,0
Exp/Cntr(USF)=0,0
Exp/Cntr=0.3,0.1

Type RM Length L Ch R = 1 ,1279    ,36.3,36.3,36.3
XS GIS Cut Line= 4
2282749.76686073570756.2578276292282967.99320786571158.516166553
2283591.27339913571363.0044182842283945.07439148571369.152629306
#Sta/Elev= 30
       0 3665.36    30.2  3653.4    64.4 3648.65    99.8 3647.83   119.4 3634.27
   135.2 3626.28   169.4 3622.67   305.9 3623.42     383  3620.6   401.5 3622.76
   491.8  3619.9     542 3623.27   554.7 3619.61   571.5 3619.44     612 3622.35
   643.1 3620.58   676.7 3621.07   697.6 3623.75     782 3623.64   857.8 3622.64
     883  3619.5   967.5 3619.46   976.6 3617.91  1013.63619.382    1021 3621.26
  1055.6 3621.74  1290.5 3621.33  1358.5 3628.03  1394.6 3633.64  1467.5 3652.39
#Mann= 3 ,-1,0
       0      .1       0   967.5    .045       0  1013.6      .1       0
#XS Ineff= 2 , 0
        534.9509    3627
Permanent Ineff=
       F       F
Bank Sta=967.5,1013.6
XS Rating Curve= 0 ,0
Exp/Cntr(USF)=0,0
Exp/Cntr=0.3,0.1

Type RM Length L Ch R = 1 ,1243    ,304.1,304.1,304.1
XS GIS Cut Line= 4
2282734.94092963570786.4116526112282946.62365271571203.393145659
2283576.44746804571393.1582432652283930.24846038571399.306454287
#Sta/Elev= 30
       0 3655.31    16.6 3651.35    41.7 3649.24    62.5 3642.96    91.1 3630.31
   115.3 3622.96   126.4    3622   205.3 3622.93   232.1 3621.24   281.2 3623.18
   348.5 3620.16   382.7 3622.05   398.7 3620.43   415.8 3622.77   451.7 3619.43
   544.2 3620.97   598.6 3619.44   719.9 3623.12   751.1 3621.11   889.8 3622.32
   977.53619.277   990.4 3617.91  1028.63619.253  1045.8 3621.76  1137.2 3622.47
  1169.9  3619.6  1333.2 3620.61  1349.2 3624.62  1417.2 3632.15  1479.3 3646.34
#Mann= 3 ,-1,0
       0      .1       0   977.5    .045       0  1028.6      .1       0
#XS Ineff= 2 , 0
          852.91 3633.13
Permanent Ineff=
       F       F
Bank Sta=977.5,1028.6
XS Rating Curve= 0 ,0
Exp/Cntr(USF)=0,0
Exp/Cntr=0.3,0.1

Type RM Length L Ch R = 1 ,939     ,342.2,342.2,342.2
XS GIS Cut Line= 4
2282693.59812826570841.526925206  2283098.762912571564.928374719
2283504.58391095 571673.449239462283956.52856885571599.047513218
#Sta/Elev= 30
       0 3641.83    31.7 3642.92    63.8 3622.26    69.2 3620.76   295.5 3622.32
   427.8 3619.42   458.1 3621.75   476.4 3619.67   531.4  3619.2   641.5 3621.11
   876.1 3620.72   892.7 3617.09   905.1 3618.87   954.8 3617.59   975.5 3619.68
   987.9 3617.14    1006  3619.2  1046.23616.734  1055.9 3615.98    10923616.827
  1134.3 3618.99  1199.1 3617.27  1219.8 3619.83  1317.7 3617.68  1508.2 3617.49
  1536.6 3619.98  1548.8 3623.48  1629.9 3633.54  1674.5 3645.39  1707.2 3651.67
#Mann= 4 ,-1,0
       0      .1       0  1046.2    .045       0    1092      .1       0
 1659.22     .06       0
Bank Sta=1046.2,1092
XS Rating Curve= 0 ,0
Exp/Cntr(USF)=0,0
Exp/Cntr=0.3,0.1

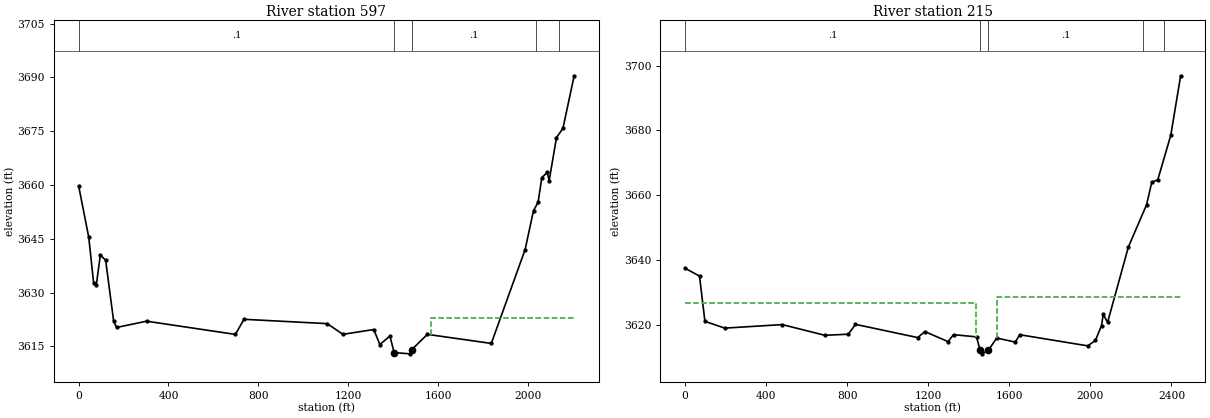
Type RM Length L Ch R = 1 ,597     ,381.4,381.4,381.4
XS GIS Cut Line= 6
2282605.69541038570821.2811306352283006.05303467571583.844016597
2283302.56486305571893.3893319412283547.21620438572019.542242979
2283704.97377299571979.736183063 2284173.2669513571880.668448802
#Sta/Elev= 30
       0 3659.76    45.1  3645.4    66.9 3632.61    78.8 3632.11    96.6 3640.46
   120.3 3639.02   155.8 3622.08   168.8 3620.27   302.6 3622.02   697.9 3618.34
   736.4 3622.55    1107 3621.34  1176.6 3618.36  1314.2  3619.7  1341.2 3615.52
  1386.2 3617.88  1404.73613.268  1476.2 3612.92  1483.43614.094  1552.8 3618.35
  1837.5 3615.82    1988 3641.97  2025.5 3652.86    2046 3655.18  2062.3 3662.04
  2086.9 3663.51    2095 3661.18  2127.7 3673.21  2156.4 3675.76  2206.5 3690.44
#Mann= 5 ,-1,0
       0      .1       0  1404.7    .045       0  1483.4      .1       0
 2037.88     .06       0 2137.88      .1       0
#XS Ineff= 2 , 0
                        1568.638            3623
Permanent Ineff=
       F       F
Bank Sta=1404.7,1483.4
XS Rating Curve= 0 ,0
Exp/Cntr(USF)=0,0
Exp/Cntr=0.3,0.1

Type RM Length L Ch R = 1 ,215     ,,,
XS GIS Cut Line= 4
 2282519.3505654570901.2725692632283043.14210753571977.176690209
2283479.92901322572209.4753441752284185.73790025571944.968548066
#Sta/Elev= 30
       0 3637.54    71.1 3635.14    97.8  3621.2   195.6 3619.11   479.3  3620.2
   689.5  3616.9   805.4 3617.24   840.7 3620.27  1147.7  3616.2  1183.3 3618.05
  1297.5 3614.95  1324.4  3617.1  1437.9 3616.41  1455.73612.292  1465.1 3611.19
  1496.3 3612.28  1537.6 3616.06  1629.2 3614.81  1650.9 3617.08  1986.4 3613.65
  2024.8 3615.31  2054.7 3619.91  2063.2 3623.34  2084.6 3620.88  2187.1 3644.08
  2276.8 3657.09  2302.5 3663.97  2332.4 3664.83  2396.4  3678.5  2445.1 3696.84
#Mann= 5 ,-1,0
       0      .1       0  1455.7    .045       0  1496.3      .1       0
 2261.35     .06       0 2361.35      .1       0
#XS Ineff= 2 , 0
         1433.01 3626.97 1539.01         3628.71
Permanent Ineff=
       F       F
Bank Sta=1455.7,1496.3
XS Rating Curve= 0 ,0
Exp/Cntr(USF)=0,0
Exp/Cntr=0.3,0.1
LCMann Table=0

Chan Stop Cuts=-1
Use User Specified Reach Order=0
Composite Channel Slope=5